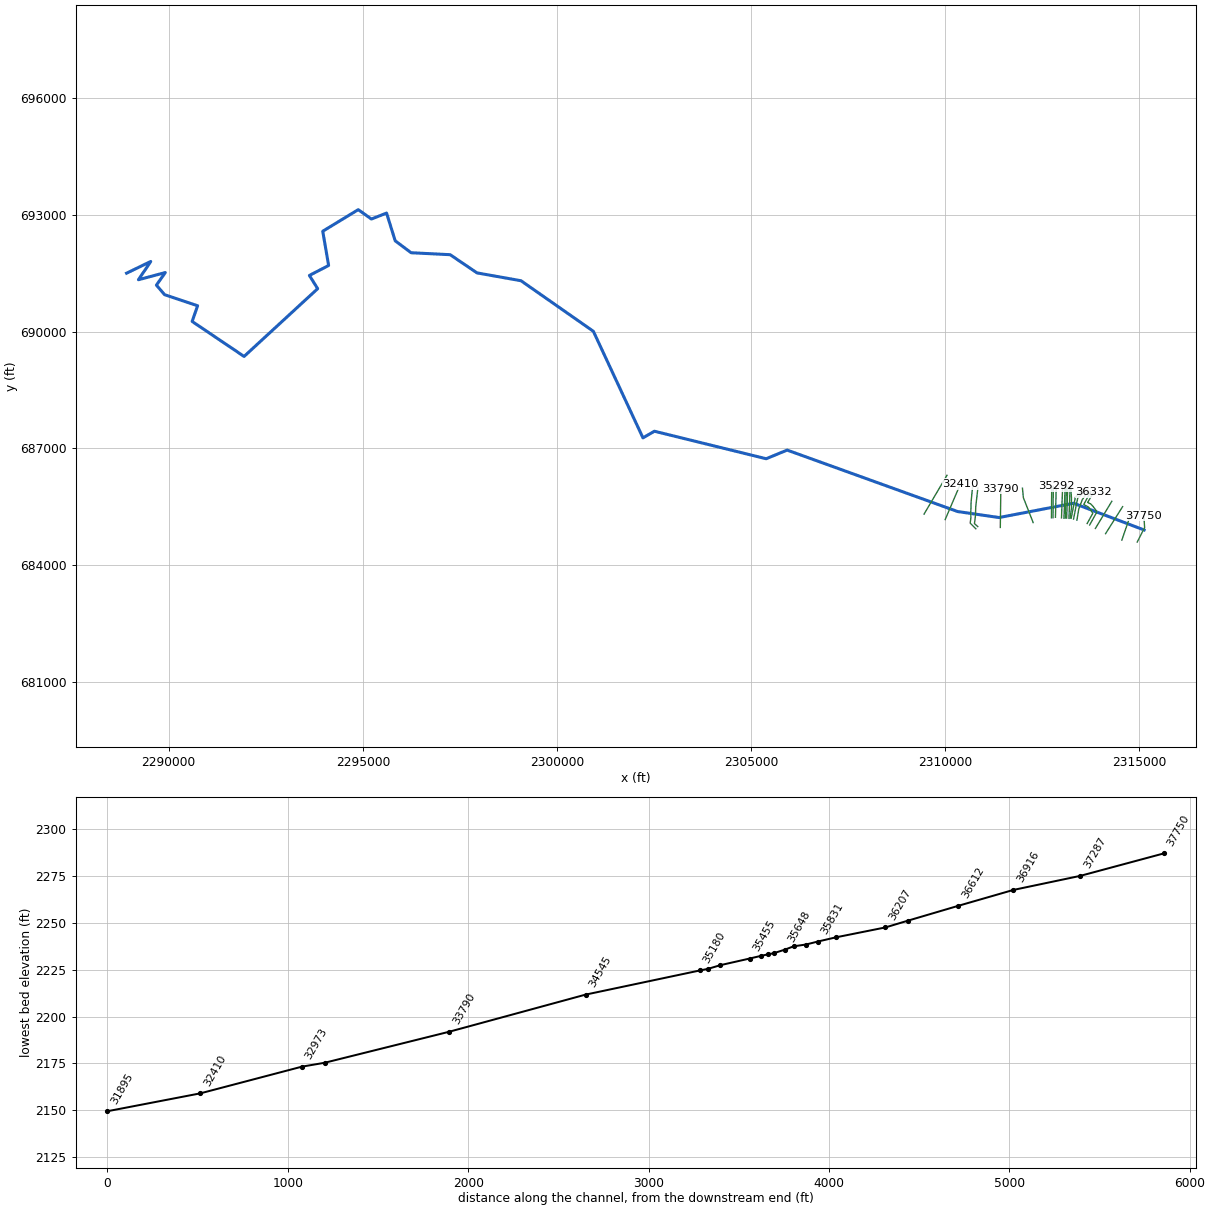
--- CHENOWTHCK.prj (project) ---

Proj Title=CHENOWTHCK
Current Plan=p01
Default Exp/Contr=0,0
English Units
Geom File=g01
Flow File=f01
Plan File=p01
BEGIN DESCRIPTION:
----------MODEL BY WSP USA 2022----------
AFH study
Randolph County, WV
HEC-RAS Version: RAS 6.2
Vertical Datum: NAVD88
Projection: NAD 1983 StatePlane West Virginia S FIPS 4702 (US Feet)
Terrain: 1-meter LIDAR (FEMA Region III 3DEP collected 2016-2018)
Land Use: 2019 NLCD
Hydrologic Method:
WV SIR2010-5033 regression equations
Additional Model Notes:
None
END DESCRIPTION:
DSS Export Rating Curves= 0
DSS Export Rating Curve Sorted= 0
DSS Export Volume Flow Curves= 0
DXF OffsetX= 0
DXF OffsetY= 0
DXF ScaleX= 0
DXF ScaleY= 0

--- CHENOWTHCK.p01 (plan) ---

Plan Title=Floodplain
Program Version=6.20
Short Identifier=Floodplain
Geom File=g01
Flow File=f01
Subcritical Flow
K Sum by GR= 0
Std Step Tol= 0.01
Critical Tol= 0.01
Num of Std Step Trials= 20
Max Error Tol= 0.3
Flow Tol Ratio= 0.001
Split Flow NTrial= 30
Split Flow Tol= 0.02
Split Flow Ratio= 0.02
Log Output Level= 0
Friction Slope Method= 1
Unsteady Friction Slope Method= 2
Unsteady Bridges Friction Slope Method= 1
Parabolic Critical Depth
Global Vel Dist= 0 , 0 , 0
Global Log Level= 0
CheckData=True
Encroach Param=-1 ,0,0, 0
Mapping Interval=1HOUR
Computation Time Step Use Courant=        0
Computation Time Step Use Time Series=    0
Computation Time Step Count To Double=0
Computation Time Step Max Doubling=0
Computation Time Step Max Halving=0
Computation Time Step Residence Courant=0
Run HTab= 0
Run UNet= 0
Run Sediment= 0
Run PostProcess= 0
Run WQNet= 0
Run RASMapper=-1
UNET Theta= 0
UNET Theta Warmup= 0
UNET ZTol= 0
UNET ZSATol= 0
UNET MxIter= 0
UNET Max Iter WO Improvement= 0
UNET MaxInSteps= 0
UNET DtIC= 0
UNET DtMin= 0
UNET MaxCRTS= 0
UNET WFStab= 0
UNET SFStab= 0
UNET WFX= 1
UNET SFX= 1
UNET Gravity=32.174
UNET 1D Methodology=Finite Difference
UNET DSS MLevel= 1
UNET Pardiso=0
UNET DZMax Abort= 0
UNET Use Existing IB Tables= 0
UNET Froude Reduction=False
UNET Froude Limit= 0
UNET Froude Power= 0
UNET D1 Cores= 0
UNET WindReference=Eulerian
UNET WindDragFormulation=Hsu (1988)
UNET D2 Coriolis=0
UNET D2 Cores= 0
UNET D2 Theta= 1
UNET D2 Theta Warmup= 1
UNET D2 Z Tol= 0.01
UNET D2 Volume Tol= 0.01
UNET D2 Max Iterations= 20
UNET D2 Equation= 0
UNET D2 RampUpFraction=0.1
UNET D2 TimeSlices= 1
UNET D2 Turbulence Formulation=Non-Conservative (original)
UNET D2 Eddy Viscosity=0.3
UNET D2 Transverse Eddy Viscosity=0.1
UNET D2 Smagorinsky Mixing=0
UNET D2 BCVolumeCheck=0
UNET D2 Cores=0
UNET D2 SolverType=PARDISO (Direct)
UNET D2 Minimum Iterations= 2147483647
UNET D2 Maximum Iterations= 2147483647
UNET D2 Restart Number= 10
UNET D2 Relaxation Coeff=1.3
UNET D2 SOR Precondition Iterations= 10
UNET D2 ILUT Maximum Fill= 8
UNET D2 ILUT Tolerance=1E-08
UNET D1D2 MaxIter= 0
UNET D1D2 ZTol=0.01
UNET D1D2 QTol=0.1
UNET D1D2 MinQTol=1
Write IC File= 0
Write IC File at Fixed DateTime=0
Write IC File at Sim End=0
Echo Input=False
Echo Parameters=False
Echo Output=False
Write Detailed= 0
HDF Write Warmup=0
HDF Write Time Slices=0
HDF Flush=0
HDF Compression= 1
HDF Chunk Size= 1
HDF Spatial Parts= 1
HDF Use Max Rows=0
HDF Fixed Rows= 1
Calibration Method= 0
Calibration Iterations= 20
Calibration Max Change=0.05
Calibration Tolerance=0.2
Calibration Maximum=1.5
Calibration Minimum=0.5
Calibration Optimization Method= 1
WQ AD Non Conservative
WQ ULTIMATE=-1
WQ Max Comp Step=1HOUR
WQ Output Interval=15MIN
WQ Output Selected Increments= 0
WQ Output face flow=0
WQ Output face velocity=0
WQ Output face area=0
WQ Output face dispersion=0
WQ Output cell volume=0
WQ Output cell surface area=0
WQ Output cell continuity=0
WQ Output cumulative cell continuity=0
WQ Output face conc=0
WQ Output face dconc_dx=0
WQ Output face courant=0
WQ Output face peclet=0
WQ Output face adv mass=0
WQ Output face disp mass=0
WQ Output cell mass=0
WQ Output cell source sink temp=0
WQ Output nsm pathways=0
WQ Output nsm derived pathways=0
WQ Create Restart=0
WQ Fixed Restart=0
WQ System Summary=0
WQ Write To DSS=0
Sorting and Armoring Iterations= 10
XS Update Threshold= 0.02
Bed Roughness Predictor= 0
Hydraulics Update Threshold= 0.02
Energy Slope Method= 1
Volume Change Method= 1
Sediment Retention Method= 0
Sediment TS Multiplier= 1
Warm Up Method= 0
XS Weighting Method= 0
Number of US Weighted Cross Sections= 1
Number of DS Weighted Cross Sections= 1
Upstream XS Weight=0
Main XS Weight=1
Downstream XS Weight=0
Number of DS XS's Weighted with US Boundary= 1
Upstream Boundary Weight= 1
Weight of XSs Associated with US Boundary= 0
Number of US XS's Weighted with DS Boundary= 1
Downstream Boundary Weight= 0.5
Weight of XSs Associated with DS Boundary= 0.5
Percentile Method= 0
Sediment Output Level= 3
Mass or Volume Output= 0
Output Increment Type= 1
Profile and TS Output Increment= 1
Transport Output Increment 1
XS Output Flag= 0
XS Output Increment= 10
Read HDF5 Sediment Hotstart= 0
Sediment Hotstart Type= 0
Write Gradation File= 0
Read Gradation Hotstart= 0
Write HDF5 File= 1
Write Binary Output= 1
Write DSS Sediment File= 0
DSS Sediment Output Type= 1
SV Curve= 0
Specific Gage Flag= 0
Subcell Erosion Methods= 0
Subcell Deposition Methods= 0
Advection Scheme= 1
Matrix Solver= 0
Implicit Weighting Factor= 1
Maximum Outer Loop Convergence Iterations= 5
Convergence Maximum Absolute= 0.001
Convergence RMSE= 0.0001
Grain Fractions Max Abs Error= 0.001
Max Subgrid Regions= 1
Max Subgrid Length Scale= 3.402823E+38
Initial Layer Thickness= 3.402823E+38
Min Layer Thickness= 3.402823E+38
Max Layer Thickness= 3.402823E+38
Number of Layers= 5

--- CHENOWTHCK.f01 (steady flow) ---

Flow Title=Flow
Program Version=4.00
Number of Profiles=1
Profile Names=P100yr
River Rch & RM=CHENOWTHCK,Main,37750
     968
River Rch & RM=CHENOWTHCK,Main,32410
    1480
River Rch & RM=CHENOWTHCK,Main,26977
    2070
River Rch & RM=CHENOWTHCK,Main,13587
    3440
Boundary for River Rch & Prof#=CHENOWTHCK,Main      ,1
Up Type=0
Dn Type=3
Dn Slope=0.001635

--- CHENOWTHCK.g01 (geometry) ---

Geom Title=Geometry
Program Version=6.20

River Reach=CHENOWTHCK      ,Main
Reach XY= 30
2315124.06275043 684899.93949574     2313307.923       685586.46
     2311389.249      685219.051     2310319.978      685373.739
     2305929.899      686952.666     2305389.249      686730.509
     2302510.461      687437.534     2302215.812      687266.968
      2300938.39      690005.887     2299074.319       691305.51
     2297941.133      691506.931     2297248.663      691974.783
     2296243.967      692024.799     2295833.551      692331.318
     2295611.298      693044.051     2295221.298      692891.187
      2294881.57      693132.427     2293967.504      692577.407
     2294118.589      691697.176     2293623.277      691441.447
     2293836.524      691101.217     2291940.937      689359.681
     2290603.202      690259.537     2290743.646      690661.968
     2289893.325      690947.115     2289682.535      691193.218
     2289912.436      691515.834      2289219.96      691330.962
     2289537.015      691800.705     2288914.055      691498.831

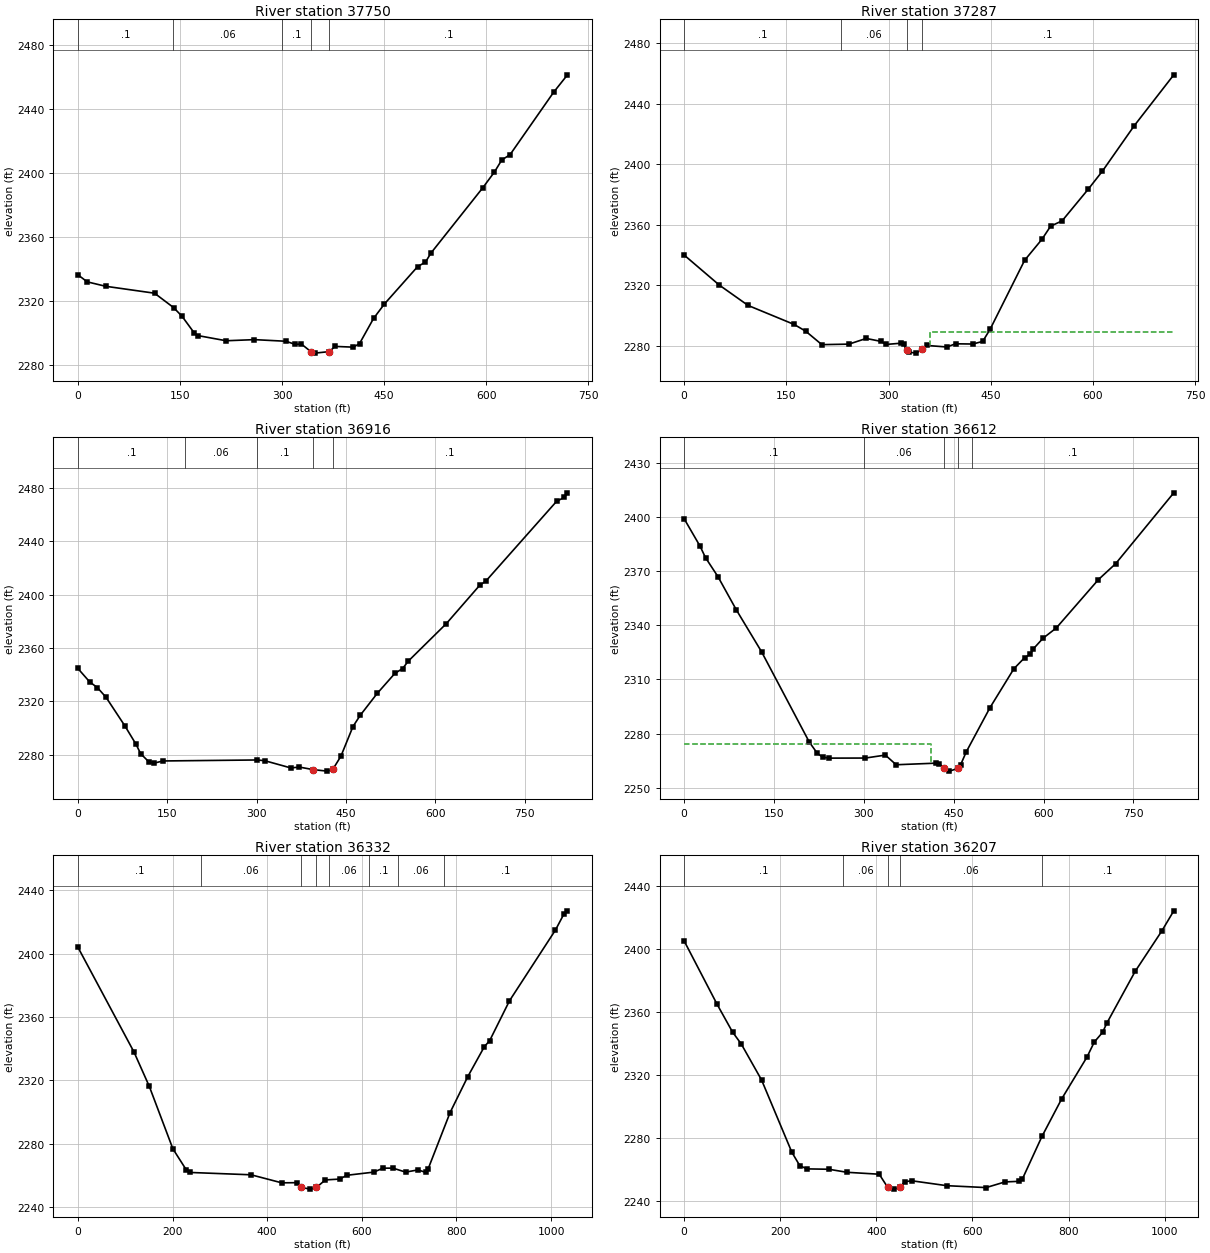
Type RM Length L Ch R = 1 ,37750   ,459.5,462.9,464.8
XS GIS Cut Line= 3
2314947.15996427684589.0053514392315138.22379906684961.947259739
2315118.01512423685261.403077734
#Sta/Elev= 30
       0 2336.25    13.7 2331.82    40.6 2329.06   112.6 2324.71   140.6 2315.69
     153 2310.25     171 2299.76   176.2 2298.17   217.8 2294.93   259.4 2295.63
   305.8 2294.61   319.3 2292.63   328.3 2292.88  342.152288.149   348.3 2287.18
   369.4 2288.14   377.7 2291.39   404.7 2290.92   413.7 2293.14   434.3 2308.89
   450.3 2317.97   499.1 2341.38   510.6 2344.19   518.5 2349.77   594.7 2390.71
   611.8 2400.56   622.7 2408.17   634.8 2411.45   698.9 2450.61   719.2 2461.48
#Mann= 5 ,-1,0
       0      .1       0     140     .06       0     300      .1       0
  342.15    .045       0   369.4      .1       0
Bank Sta=342.15,369.4
XS Rating Curve= 0 ,0
Exp/Cntr(USF)=0,0
Exp/Cntr=0.3,0.1

Type RM Length L Ch R = 1 ,37287   ,373.7,371.4,369
XS GIS Cut Line= 2
2314552.17222888684640.445614653 2314785.4905656685320.191949978
#Sta/Elev= 30
       0 2339.93    51.5 2320.14    93.8 2306.68   161.5 2294.11   178.4 2289.67
   202.1 2280.79   241.8 2281.13   267.2 2284.88   288.4 2282.99   296.8 2280.94
   318.6 2281.76   322.2 2281.16   326.4 2277.49   330.6 2275.79   340.6 2275.19
   349.42277.626   356.3 2280.24   385.6 2279.25   398.3 2281.35   423.7  2281.2
   438.2 2282.93   449.1 2290.95   499.8 2336.52   525.2 2350.36   537.9 2359.01
   554.8 2362.55   592.8 2383.25     614 2395.39   660.5 2425.25   718.7 2458.95
#Mann= 4 ,-1,0
       0      .1       0     230     .06       0   326.4    .045       0
   349.4      .1       0
#XS Ineff= 2 , 0
                          360.39         2289.27
Permanent Ineff=
       F       F
Bank Sta=326.4,349.4
XS Rating Curve= 0 ,0
Exp/Cntr(USF)=0,0
Exp/Cntr=0.3,0.1

Type RM Length L Ch R = 1 ,36916   ,304.1,303.9,304.1
XS GIS Cut Line= 2
2314131.94160089684804.3469016022314570.97121419 685499.18904548
#Sta/Elev= 30
       0  2344.6    19.9 2334.49    32.7 2330.27    47.2 2323.04    79.1 2301.42
    97.8 2287.62   105.3 2280.76   119.3 2274.55   127.7 2273.63   142.7 2275.28
     300 2276.02   313.3 2275.53   357.4 2270.06   371.9 2270.69   395.1 2268.78
   418.3 2267.66   427.82268.895   441.5 2278.82   461.8  2301.1   474.1 2309.58
   502.5 2325.93   532.1  2340.9   545.1 2344.54   554.6  2350.1   618.4 2378.18
   674.4 2406.88   685.1 2410.23   803.9 2470.04   816.7 2472.81   821.9 2476.27
#Mann= 5 ,-1,0
       0      .1       0     180     .06       0     300      .1       0
   395.1    .045       0   427.8      .1       0
Bank Sta=395.1,427.8
XS Rating Curve= 0 ,0
Exp/Cntr(USF)=0,0
Exp/Cntr=0.3,0.1

Type RM Length L Ch R = 1 ,36612   ,267.6,280.2,300.7
BEGIN DESCRIPTION:
Structure XS 4
END DESCRIPTION:
XS GIS Cut Line= 2
2313869.45043035684938.6345675512314293.34774611 685637.41437695
#Sta/Elev= 30
       0 2398.89    26.4  2383.8    35.7 2377.34    56.3 2366.92    87.2  2348.4
   129.1 2325.34   208.8 2275.33   222.2 2269.09     231 2266.98   241.6 2266.42
   302.4 2266.46   335.8  2268.1   353.9 2262.75   420.2 2263.63   426.1 2263.19
  434.152260.719   442.8 2259.22   456.8 2260.71   461.5 2262.75   470.8 2269.83
   510.5 2294.37   550.4  2315.9   568.2 2321.98   577.5 2323.87   583.1 2326.98
   599.1  2332.8   621.2 2338.48   691.6 2365.28   720.2 2374.03   817.3 2413.28
#Mann= 5 ,-1,0
       0      .1       0     300     .06       0  434.15    .045       0
   456.8     .06       0     480      .1       0
#XS Ineff= 2 , 0
          411.36 2274.46
Permanent Ineff=
       F       F
Bank Sta=434.15,456.8
XS Rating Curve= 0 ,0
Exp/Cntr(USF)=0,0
Exp/Cntr=0.3,0.1

Type RM Length L Ch R = 1 ,36332   ,127.5,124.7,122.1
BEGIN DESCRIPTION:
Structure XS 3
END DESCRIPTION:
XS GIS Cut Line= 6
2313722.74634755685029.4179120482313911.73420029685368.703190988
2313806.07957396685510.0720572142313749.53202747685568.107697032
2313670.66308105685608.2862169072313822.44860057685867.214456098
#Sta/Elev= 30
       0    2404   118.5 2337.85   150.9 2316.15   200.8 2276.69   228.7 2263.61
   237.8 2261.78     366 2260.31   430.9 2255.23   463.4 2255.34   471.8 2252.33
   491.4 2251.26   504.2 2252.33     523 2257.07   553.8 2257.62   567.9 2259.98
   625.2 2261.99   645.1 2264.51   666.2  2264.5   692.6    2262     719 2263.41
   735.7 2261.77   740.4 2264.13   786.7 2299.64   824.1  2322.3   859.2 2341.26
   870.2 2344.94   912.2 2370.17  1009.3 2414.81  1027.8 2425.27  1034.8 2426.97
#Mann= 8 ,-1,0
       0      .1       0     260     .06       0   471.8    .045       0
   504.2      .1       0  531.75     .06       0  615.15      .1       0
  676.18     .06       0   774.7      .1       0
Bank Sta=471.8,504.2
XS Rating Curve= 0 ,0
Exp/Cntr(USF)=0,0
Exp/Cntr=0.3,0.1

Type RM Length L Ch R = 1 ,36207   ,282.2,276.4,259.8
BEGIN DESCRIPTION:
Structure XS 2
END DESCRIPTION:
XS GIS Cut Line= 6
2313657.27024109685065.132151936 2313803.1033873685328.524671114
2313709.35350759685472.8697239962313654.29405443685510.072057214
 2313569.4727347685551.738670417 2313751.0201208685891.023949357
#Sta/Elev= 30
       0 2405.24    68.6 2364.97   100.6 2347.44   118.9 2339.77   161.1 2316.96
   224.1 2271.07   240.5 2262.59   255.3 2260.51   301.1 2260.27   338.8 2258.34
   405.9 2257.12  423.26 2248.93   436.9 2247.65   449.5    2249   459.1 2252.29
   473.3 2252.97   546.6 2249.84   628.4 2248.63   667.6 2252.22   696.4  2252.6
   703.9 2254.09   744.7 2281.16   785.6 2304.92   838.3 2331.49   853.6 2341.09
   870.8 2347.21   879.6 2353.03   938.7 2385.99   994.3  2411.7    1019  2424.4
#Mann= 5 ,-1,0
       0      .1       0  331.07     .06       0  423.26    .045       0
   449.5     .06       0  744.24      .1       0
Bank Sta=423.26,449.5
XS Rating Curve= 0 ,0
Exp/Cntr(USF)=0,0
Exp/Cntr=0.3,0.1

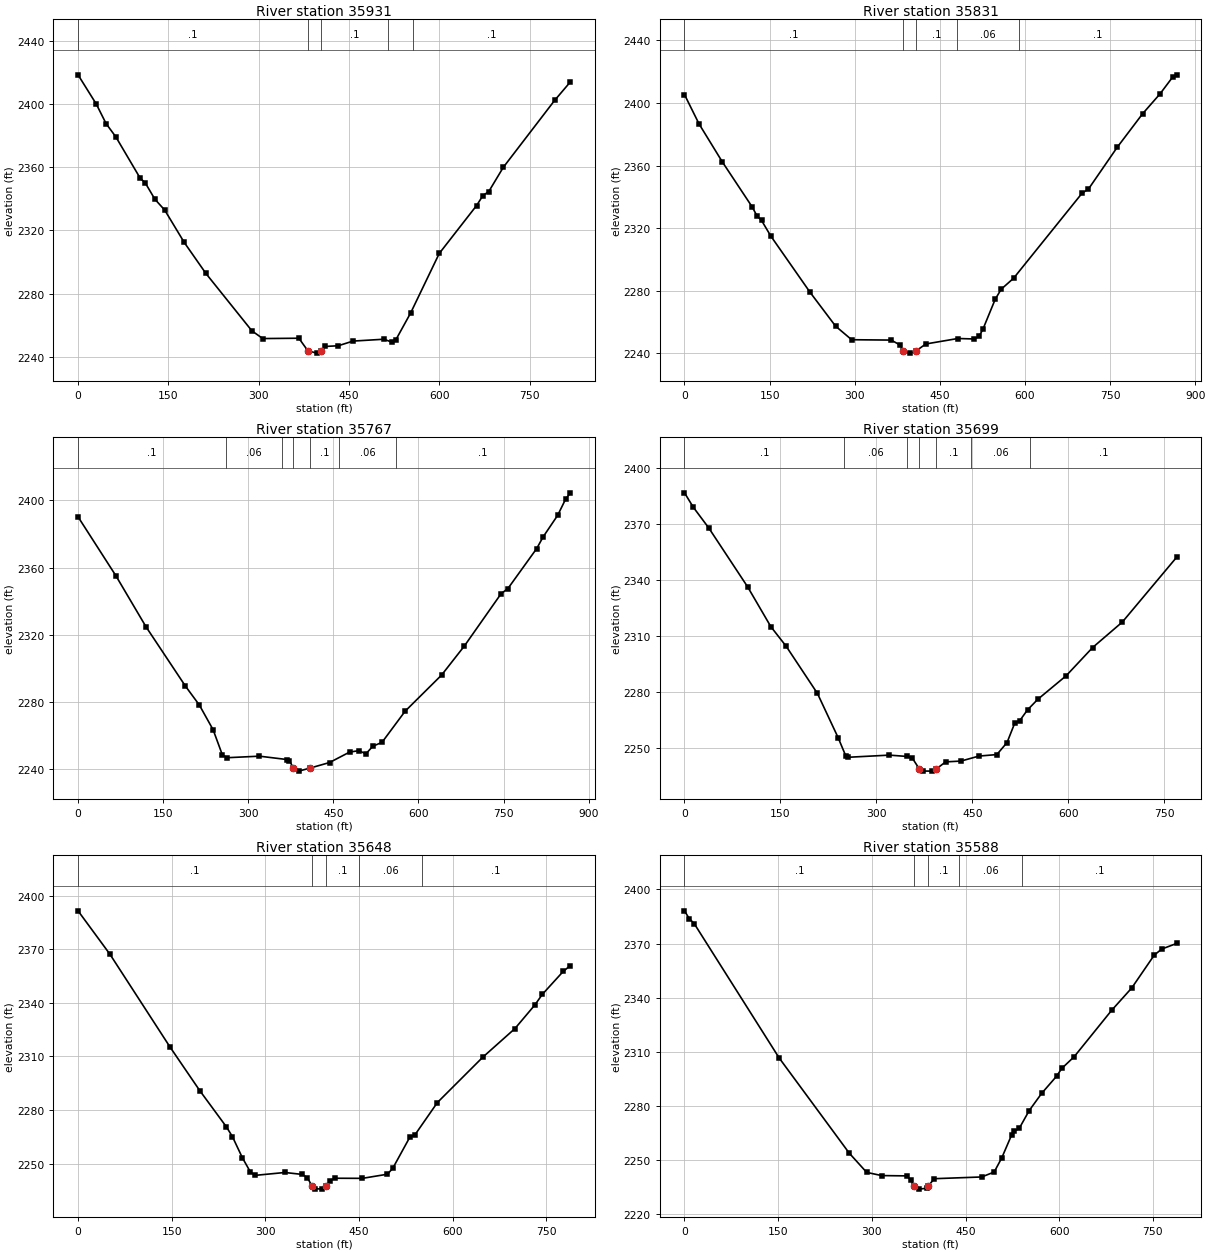
Type RM Length L Ch R = 1 ,35931   ,97.7,99.8,101.4
XS GIS Cut Line= 4
2313393.79317822685151.2169029172313442.24067163685441.901863407
2313531.95825203 685676.961924052313684.47813871685901.255875046
#Sta/Elev= 30
       0 2418.48    30.4 2399.92    46.6 2387.58    62.8 2379.19   103.4 2352.92
   111.5 2350.15   127.7 2339.69   143.9 2332.88   176.4 2312.35   212.3 2292.76
   288.8 2256.38   306.8 2251.53   366.7 2251.74   381.82243.709   396.7 2242.31
  404.19 2243.63   410.3 2246.54     432 2246.97   456.6 2249.93     508 2251.11
   520.8 2249.29     528 2250.93   552.4 2267.81   599.8  2305.4   661.8 2335.74
   672.3 2342.04     682 2344.59   706.2 2359.95   791.3 2402.26   817.5 2413.99
#Mann= 5 ,-1,0
       0      .1       0   381.8    .045       0  404.19      .1       0
  514.69     .06       0  556.29      .1       0
Bank Sta=381.8,404.19
XS Rating Curve= 0 ,0
Exp/Cntr(USF)=0,0
Exp/Cntr=0.3,0.1

Type RM Length L Ch R = 1 ,35831   ,63.8,63.8,64.5
BEGIN DESCRIPTION:
Structure XS 1
END DESCRIPTION:
XS GIS Cut Line= 3
2313306.94397383685180.0013111852313414.10868259 685719.28178106
2313645.72273055685937.068124664
#Sta/Elev= 30
       0 2405.33    25.7 2386.55    66.7  2362.3   119.5 2333.41   127.6 2327.89
   135.8 2324.88   152.1 2314.91   221.4 2278.91   266.3 2257.31   294.6 2248.64
   364.2 2248.41   379.7 2245.31  385.76 2241.34   396.7 2240.07  407.56 2241.34
   425.3 2245.92   481.8 2249.42     511 2249.11   519.2  2250.8     526 2255.39
   547.7 2274.56   558.2 2280.94   580.1 2287.98   700.9 2342.39   711.9 2344.92
   762.8 2371.73   807.3 2393.05   838.2 2405.84   860.1 2416.41   867.7 2417.97
#Mann= 5 ,-1,0
       0      .1       0  385.76    .045       0  407.56      .1       0
     480     .06       0  589.83      .1       0
Bank Sta=385.76,407.56
XS Rating Curve= 0 ,0
Exp/Cntr(USF)=0,0
Exp/Cntr=0.3,0.1

Type RM Length L Ch R = 1 ,35767   ,65.8,68.5,71.9
BEGIN DESCRIPTION:
Structure XS 1
END DESCRIPTION:
XS GIS Cut Line= 3
2313245.78350514685199.621492721 2313352.9482139685738.901962596
2313584.56226186  685956.6883062
#Sta/Elev= 30
       0 2390.25    66.8 2355.04   119.9 2324.58   189.2 2289.28   213.7 2278.01
   238.1  2263.2   254.4 2248.18   262.6 2246.52   319.8 2247.44   368.6 2245.42
   372.7 2244.71  379.47 2240.38     389 2238.52   409.4 2240.39   443.2 2243.64
   478.7 2249.89   495.1 2250.73   507.3 2248.82   519.5 2253.35   535.8 2255.71
   576.5 2274.28   640.7 2295.81   681.1 2313.27   745.8 2344.46   757.5 2347.39
   808.4 2371.33   819.7 2378.27   845.3 2391.12   859.3 2400.76   867.7 2404.56
#Mann= 7 ,-1,0
       0      .1       0     260     .06       0     360      .1       0
  379.47    .045       0   409.4      .1       0     460     .06       0
  559.83      .1       0
Bank Sta=379.47,409.4
XS Rating Curve= 0 ,0
Exp/Cntr(USF)=0,0
Exp/Cntr=0.3,0.1

Type RM Length L Ch R = 1 ,35699   ,51.2,50.7,50.4
XS GIS Cut Line= 4
2313217.89109574685207.5218620232313254.51740076685462.597914853
2313253.20931844685725.5224616172313237.51233057685974.058102836
#Sta/Elev= 30
       0  2386.6    13.8 2378.87      38 2367.76    98.7 2336.25     135 2314.92
     159 2304.41   207.8 2279.19   240.1 2255.55   252.2 2245.66   256.3 2244.99
   320.3 2246.13   348.3 2245.41   356.3 2244.48     367 2238.78   372.3 2237.62
   386.6 2237.56   393.9 2238.79   408.3 2242.51   432.3 2242.95   460.3 2245.62
   488.3 2246.42   504.3 2252.89   516.3 2263.28   524.3 2264.67   536.3 2270.37
   552.3 2276.01   596.7 2288.64   638.1 2303.76   684.6 2317.43   769.7 2352.22
#Mann= 7 ,-1,0
       0      .1       0     250     .06       0  347.69      .1       0
     367    .045       0   393.9      .1       0  447.69     .06       0
  540.62      .1       0
Bank Sta=367,393.9
XS Rating Curve= 0 ,0
Exp/Cntr(USF)=0,0
Exp/Cntr=0.3,0.1

Type RM Length L Ch R = 1 ,35648   ,59.9,59.9,59.9
XS GIS Cut Line= 2
2313189.14737733685198.2378868032313217.85700306  685985.9582427
#Sta/Elev= 30
       0 2391.45      51 2367.19     147 2315.38     195 2290.79   237.5 2270.58
   247.1 2265.15   263.1 2253.28   276.1 2245.21   283.8 2243.43   331.2 2245.03
   359.2 2243.94   367.2 2242.09     3752237.255   379.2 2235.98   391.2 2235.72
  396.77 2237.22   403.2 2240.49   411.2 2241.81   455.2 2241.75   495.3 2244.06
   503.9 2247.39   531.3 2264.86   539.3 2266.05   575.3 2284.17   647.9 2309.51
   699.4 2325.54   731.4 2338.79   743.4 2344.74   776.7 2357.52   788.2 2360.83
#Mann= 5 ,-1,0
       0      .1       0     375    .045       0  396.77      .1       0
     450     .06       0     550      .1       0
Bank Sta=375,396.77
XS Rating Curve= 0 ,0
Exp/Cntr(USF)=0,0
Exp/Cntr=0.3,0.1

Type RM Length L Ch R = 1 ,35588   ,34.3,33.8,33.8
XS GIS Cut Line= 2
2313129.50851294685205.6844459772313158.21813867685993.404801873
#Sta/Elev= 30
       0 2388.14     7.5 2383.86    15.5 2381.08   151.6 2306.56   263.7 2253.85
   291.7 2243.15   315.7 2241.39   355.7 2241.22   362.3 2238.91   367.7 2235.56
   375.7 2233.88   387.8 2234.38  390.17 2235.56   399.8 2239.66   475.8 2240.62
   495.8 2243.36     508 2251.25   523.8 2263.97   527.8 2265.93   535.9 2267.55
   551.9 2277.45   571.9    2287   595.9 2296.55   603.9 2300.75   623.9 2307.29
   683.9 2333.01     716 2345.38     752 2363.57     764 2366.95   788.2 2370.09
#Mann= 5 ,-1,0
       0      .1       0   367.7    .045       0  390.17      .1       0
     440     .06       0     540      .1       0
Bank Sta=367.7,390.17
XS Rating Curve= 0 ,0
Exp/Cntr(USF)=0,0
Exp/Cntr=0.3,0.1

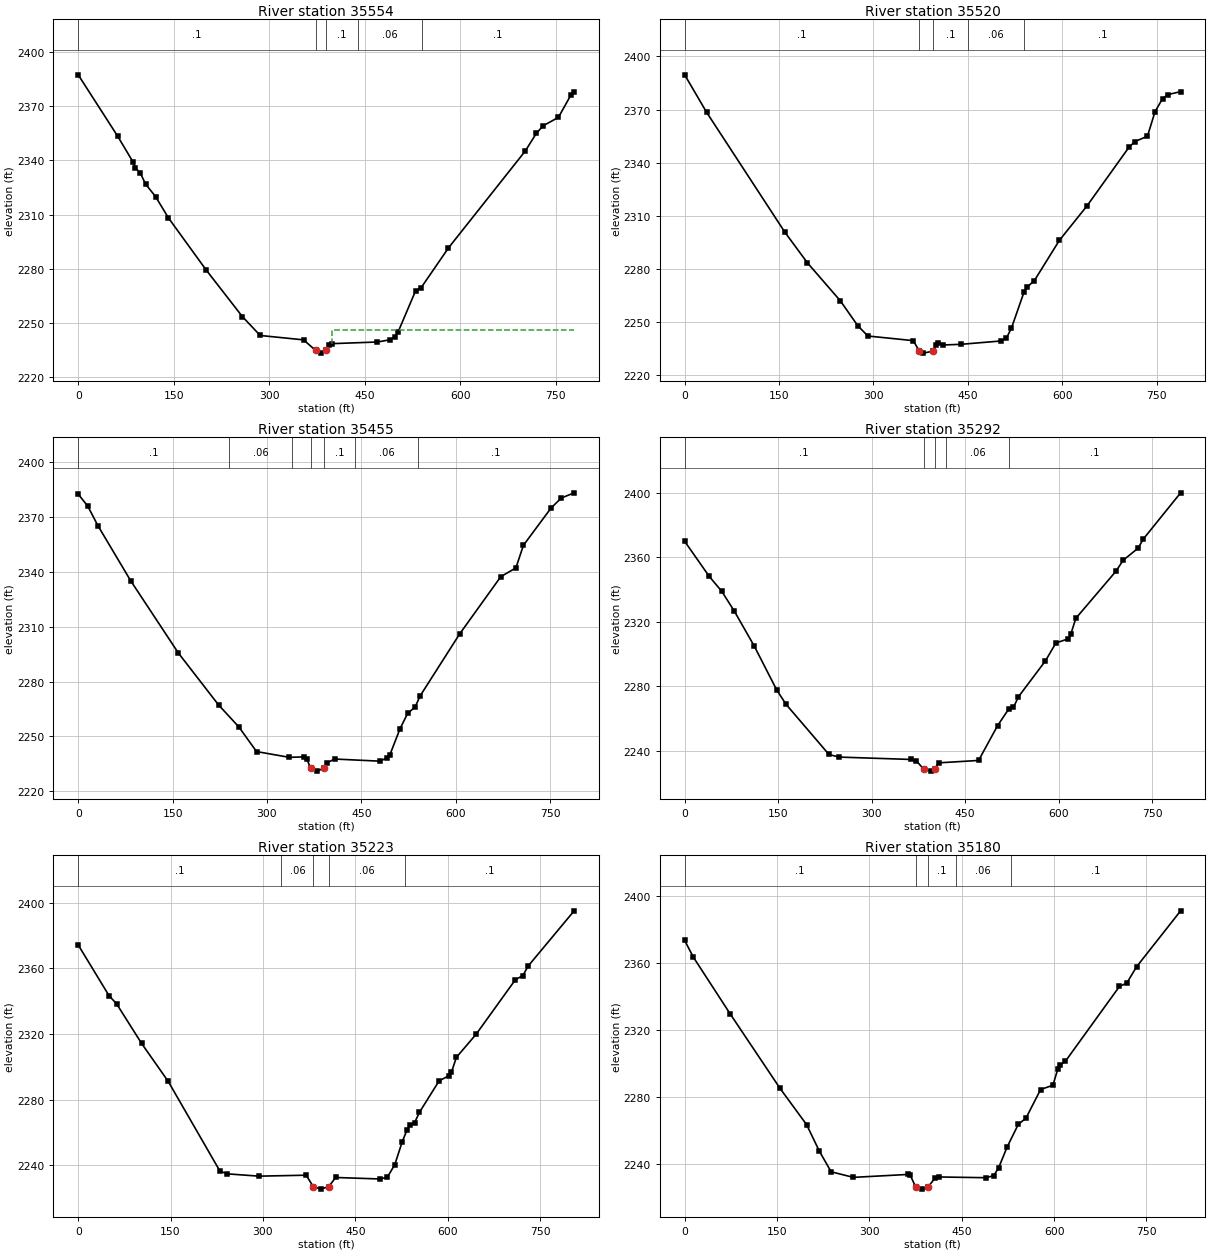
Type RM Length L Ch R = 1 ,35554   ,35.3,34.6,34.6
XS GIS Cut Line= 2
2313096.23943977685207.5218620232313123.70916854685985.830843736
#Sta/Elev= 30
       0 2387.43    61.7 2353.56    85.7 2339.37    89.7 2335.94    97.7 2332.91
   105.7 2326.92   121.4 2319.99   141.7 2308.15   200.9 2279.31   257.8 2253.47
   285.8 2243.01   353.9 2240.58   372.7 2234.75   381.9 2233.23  388.86 2234.77
   393.9 2237.82   397.9 2238.47   469.9  2239.4     490 2240.65     498  2242.4
     502 2244.68     530 2267.93     538 2269.24   581.4 2291.51   702.1 2345.25
   719.5 2355.05   730.1  2359.2   754.1 2363.86   774.1 2376.48   778.8 2377.86
#Mann= 5 ,-1,0
       0      .1       0   372.7    .045       0  388.86      .1       0
     440     .06       0     540      .1       0
#XS Ineff= 2 , 0
                          398.37         2245.93
Permanent Ineff=
       F       F
Bank Sta=372.7,388.86
XS Rating Curve= 0 ,0
Exp/Cntr(USF)=0,0
Exp/Cntr=0.3,0.1

Type RM Length L Ch R = 1 ,35520   ,64.4,64.4,64.4
XS GIS Cut Line= 2
2313060.95530975 685202.162133772313089.66493548685989.882489666
#Sta/Elev= 30
       0 2389.62      35 2368.38   159.1 2300.84   195.1 2283.47   247.2 2262.13
   275.2 2247.94   291.2 2242.17   363.3 2239.56   372.9 2233.71   379.3 2232.51
   395.3 2233.68   399.3 2237.01   403.3 2238.34   411.3 2237.12   438.6 2237.47
   503.4 2239.39   511.4 2240.99   519.4 2246.71   539.4 2267.07   543.4 2269.61
   555.4 2273.24   595.4 2296.12   639.4 2315.62     706 2348.68   715.5 2351.94
   735.5 2354.97   747.5 2368.78   759.5 2376.18   767.5  2378.4   788.2 2380.14
#Mann= 5 ,-1,0
       0      .1       0   372.9    .045       0   395.3      .1       0
     450     .06       0     540      .1       0
Bank Sta=372.9,395.3
XS Rating Curve= 0 ,0
Exp/Cntr(USF)=0,0
Exp/Cntr=0.3,0.1

Type RM Length L Ch R = 1 ,35455   ,162.9,163,162.5
XS GIS Cut Line= 2
2312996.85927597685210.0106277032313025.56890169  685997.7309836
#Sta/Elev= 30
       0 2382.37    15.2  2375.8    31.2  2365.2    83.2 2335.15   159.3  2295.5
   223.3  2267.1   255.3 2255.19   283.4 2241.73   335.4 2238.58   359.4 2238.82
   363.4 2237.55   369.6 2232.56   379.4 2231.04  389.99 2232.54   395.4 2235.54
   407.4 2237.65   479.5 2236.48   491.5 2238.39   495.5 2240.09   511.5 2254.23
   523.5 2262.54   535.5  2266.1   543.5 2272.19   606.3 2306.02   671.6 2337.27
   695.6 2342.06   707.6 2354.43   751.7 2374.87   767.7 2380.22   788.2 2383.08
#Mann= 7 ,-1,0
       0      .1       0     240     .06       0     340      .1       0
   369.6    .045       0  389.99      .1       0     440     .06       0
     540      .1       0
Bank Sta=369.6,389.99
XS Rating Curve= 0 ,0
Exp/Cntr(USF)=0,0
Exp/Cntr=0.3,0.1

Type RM Length L Ch R = 1 ,35292   ,70.2,69.7,69.4
XS GIS Cut Line= 2
2312841.16338694685225.8350145342312860.78462178686021.149066435
#Sta/Elev= 30
       0 2369.92    39.4 2348.18    59.4 2338.98    79.4  2326.8   111.4 2305.16
   147.4 2277.98   162.4 2268.99   231.4 2237.84   247.4  2236.2   363.5 2234.72
   371.5 2233.91   383.5  2228.7   395.5 2227.49  400.82 2228.71   407.5 2232.62
   471.5 2234.11   502.1 2255.77   519.5 2265.78   527.5 2267.08   535.5  2273.6
   578.8 2295.87   595.5 2306.92   615.5 2309.52   619.5 2312.52   627.5  2322.2
   691.6 2351.27   703.6 2358.26   727.6 2365.75   735.6 2371.28   795.6 2399.99
#Mann= 5 ,-1,0
       0      .1       0   383.5    .045       0  400.82      .1       0
     420     .06       0     520      .1       0
Bank Sta=383.5,400.82
XS Rating Curve= 0 ,0
Exp/Cntr(USF)=0,0
Exp/Cntr=0.3,0.1

Type RM Length L Ch R = 1 ,35223   ,42,42.6,43.4
XS GIS Cut Line= 2
2312778.46235381685215.0164316252312785.37620599 686020.48021035
#Sta/Elev= 30
       0 2374.18    50.2 2343.21    62.2 2338.39     103 2314.18   146.2 2291.07
   230.2 2236.44   242.2 2234.78   293.4 2233.38   370.2 2233.96   381.82227.025
   394.2 2225.48  406.87 2227.03   418.2 2232.57   490.2 2231.66   502.2  2232.8
   514.2 2240.42   526.2 2254.28   534.2 2261.65   538.2 2264.38   546.2 2265.83
   554.2 2272.25   586.2 2291.42   602.2 2294.57   606.2 2296.66   614.2 2305.71
   646.4 2319.86   710.2 2353.09   722.2 2355.48   730.7 2361.29   805.5 2394.96
#Mann= 5 ,-1,0
       0      .1       0     330     .06       0   381.8    .045       0
  406.87     .06       0     530      .1       0
Bank Sta=381.8,406.87
XS Rating Curve= 0 ,0
Exp/Cntr(USF)=0,0
Exp/Cntr=0.3,0.1

Type RM Length L Ch R = 1 ,35180   ,630.6,635,639.4
XS GIS Cut Line= 2
2312737.90964511 685211.127736962312744.82349729686016.591515685
#Sta/Elev= 30
       0 2373.44    14.1 2363.44    74.1  2329.4     155 2284.89   198.1 2263.23
   218.4 2247.65   237.8 2235.07     274 2231.72   362.9 2233.48   366.1 2233.22
     375 2226.12     385 2224.69  395.51 2226.07   406.1 2231.07   412.8 2231.96
   490.1 2231.52   502.1 2232.83   510.1 2237.61   523.8 2249.95   542.1 2263.61
   554.1    2267   578.1 2284.28   598.1 2286.83   606.1 2296.66   610.1 2299.06
   618.1 2301.04   706.1 2345.91   718.1 2347.97     734 2357.73   805.5 2391.17
#Mann= 5 ,-1,0
       0      .1       0     375    .045       0  395.51      .1       0
     440     .06       0     530      .1       0
Bank Sta=375,395.51
XS Rating Curve= 0 ,0
Exp/Cntr(USF)=0,0
Exp/Cntr=0.3,0.1

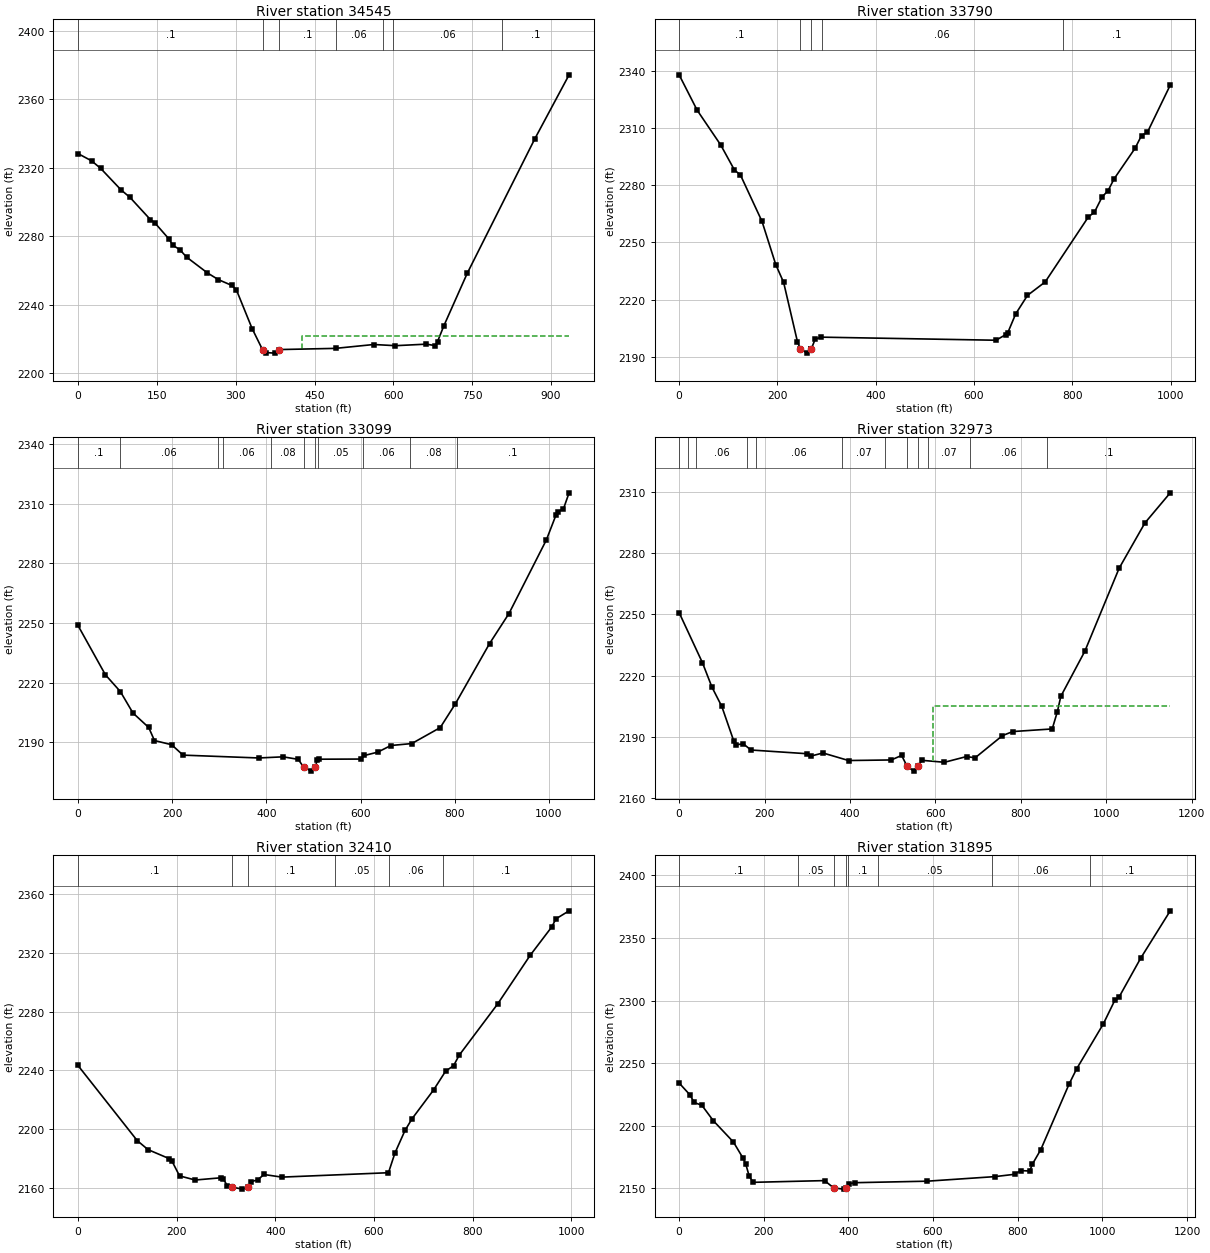
Type RM Length L Ch R = 1 ,34545   ,759.1,755.2,749.1
XS GIS Cut Line= 3
2312267.47342197685088.9998578742312015.11781748685728.531184329
2311990.91933486685973.972936644
#Sta/Elev= 30
       0 2328.35      26 2324.08    43.2 2319.68    81.9 2307.14    99.1 2302.69
   137.8 2289.76   146.4  2287.8   172.3 2278.72   180.8 2274.68   193.7 2272.23
   206.6 2267.85   246.3 2258.61   266.8 2254.74   292.3 2251.35   301.2 2248.83
   331.3 2226.07   351.1 2213.73   357.1 2212.07   374.3 2211.75   382.9 2213.83
   489.9 2214.53   562.7 2216.79     604  2216.1   662.8    2217   679.6 2216.13
   683.9 2218.45   696.2 2227.86   740.4 2258.35     869 2336.96   934.2 2374.36
#Mann= 7 ,-1,0
       0      .1       0   351.1    .045       0   382.9      .1       0
     490     .06       0     580     .05       0     600     .06       0
  807.52      .1       0
#XS Ineff= 2 , 0
                          425.58         2221.64
Permanent Ineff=
       F       F
Bank Sta=351.1,382.9
XS Rating Curve= 0 ,0
Exp/Cntr(USF)=0,0
Exp/Cntr=0.3,0.1

Type RM Length L Ch R = 1 ,33790   ,690.9,690.5,691.3
BEGIN DESCRIPTION:
Structure XS 4
END DESCRIPTION:
XS GIS Cut Line= 2
2311420.52653018684964.5505186722311434.35423454685963.602158378
#Sta/Elev= 30
       0 2337.89    36.6 2319.37    84.6 2301.11   112.6 2287.94   124.6 2285.43
   168.6 2261.03   196.6 2238.36   212.6 2229.03   240.7 2197.93  246.862193.993
   260.6 2191.94   268.7 2193.97   268.7 2194.02   276.7 2199.22   288.7 2200.32
   644.7  2198.7   664.7 2201.69   668.7 2202.69   684.7 2212.52   708.7 2222.22
   744.7 2229.28   832.7 2263.42   844.8  2265.8   860.5 2273.86   872.7 2277.17
   884.7 2283.26   927.5 2299.35   940.7 2306.07   952.7 2307.78   999.1 2332.49
#Mann= 5 ,-1,0
       0      .1       0  246.86    .045       0   268.7      .1       0
     290     .06       0     780      .1       0
Bank Sta=246.86,268.7
XS Rating Curve= 0 ,0
Exp/Cntr(USF)=0,0
Exp/Cntr=0.3,0.1

Type RM Length L Ch R = 1 ,33099   ,126.2,126.3,125.8
BEGIN DESCRIPTION:
Structure XS 3
END DESCRIPTION:
XS GIS Cut Line= 6
2310840.36583515684986.3464376632310753.25129771685064.127274664
2310768.80746511685163.6867460262310781.25239903685285.024851748
2310787.47486599685490.3662614312310843.47706863 685985.05238476
#Sta/Elev= 30
       0 2248.75    58.3 2223.88      90 2215.44   116.8 2204.63   150.2 2197.35
   162.4 2190.77   198.8 2188.67   223.1 2183.42   383.7 2181.99   435.7 2182.56
   467.7 2181.29   479.52177.239   495.8 2175.36   503.8  2177.2   507.8    2181
   511.8 2181.37   600.1 2181.44   608.2 2183.24   636.4 2184.92   664.5 2188.27
   708.8 2189.25   769.2 2197.29   801.3 2209.26   873.9 2239.61   915.1 2254.74
   994.6 2291.86  1014.9 2304.32  1018.8 2306.01  1030.9 2307.53  1042.8 2315.57
#Mann= 11 ,-1,0
       0      .1       0      90     .06       0  297.55      .1       0
  307.55     .06       0  409.53     .08       0   479.5    .045       0
   503.8     .08       0  509.53     .05       0  604.96     .06       0
  704.96     .08       0  804.96      .1       0
Bank Sta=479.5,503.8
XS Rating Curve= 0 ,0
Exp/Cntr(USF)=0,0
Exp/Cntr=0.3,0.1

Type RM Length L Ch R = 1 ,32973   ,567.9,563,555.7
BEGIN DESCRIPTION:
Structure XS 2
END DESCRIPTION:
XS GIS Cut Line= 6
2310790.58609947684930.344235022 2310644.3581259685076.572208585
2310663.02552678685210.3552482272310659.91429331685350.360754829
2310669.24799374685630.3717680342310706.58279551 686016.16471956
#Sta/Elev= 30
       0 2250.87    54.6 2226.33    76.9 2214.37    99.9 2204.94   127.9 2188.04
   133.5 2186.22   150.5 2186.61   168.1 2183.62   300.3 2181.79   308.4 2180.64
   336.7 2182.17   396.7 2178.47   496.7 2178.75   520.8 2180.96   533.3 2175.83
   548.8 2173.28   559.1 2175.87   568.8 2178.56   621.2 2177.61   672.8 2180.41
   692.9 2179.79   756.9 2190.66     781 2192.65   873.4 2193.93   885.5 2202.39
   893.5 2209.87   949.8 2231.98  1030.1 2272.61  1090.4 2294.75  1149.7  2309.5
#Mann= 12 ,-1,0
       0      .1       0      20     .08       0      40     .06       0
     160     .05       0     180     .06       0  381.88     .07       0
  481.88      .1       0   533.3    .045       0   559.1      .1       0
  581.92     .07       0  681.92     .06       0  862.08      .1       0
#XS Ineff= 2 , 0
                          594.02         2205.11
Permanent Ineff=
       F       F
Bank Sta=533.3,559.1
XS Rating Curve= 0 ,0
Exp/Cntr(USF)=0,0
Exp/Cntr=0.3,0.1

Type RM Length L Ch R = 1 ,32410   ,516.5,515.2,513.1
BEGIN DESCRIPTION:
Structure XS 1
END DESCRIPTION:
XS GIS Cut Line= 2
2310000.33279553685166.7979795062310392.34821402686081.500622641
#Sta/Elev= 30
       0 2243.36   120.1 2192.11   141.9 2185.98   185.4 2179.74   190.6 2178.05
   205.8 2168.06   237.6 2165.23   289.8 2166.76   294.2 2166.09   302.9 2161.23
   311.6 2160.43   333.3 2159.02  344.352160.577   350.7 2164.08   364.2 2165.35
   376.9    2169   412.9 2167.21   629.2 2170.21   642.3 2183.64   662.7 2199.04
   677.1 2207.08   720.6 2226.65     745 2239.47   761.2 2243.24   772.4 2250.31
   850.2  2285.2   916.5 2318.56     960 2337.82   968.7  2343.4   995.2 2348.84
#Mann= 6 ,-1,0
       0      .1       0   311.6    .045       0  344.35      .1       0
     520     .05       0     630     .06       0     740      .1       0
Bank Sta=311.6,344.35
XS Rating Curve= 0 ,0
Exp/Cntr(USF)=0,0
Exp/Cntr=0.3,0.1

Type RM Length L Ch R = 1 ,31895   ,458.8,454.5,446.1
BEGIN DESCRIPTION:
Structure XS 4
END DESCRIPTION:
XS GIS Cut Line= 2
2309455.86693653685306.8034861082310047.00129773686305.509433205
#Sta/Elev= 30
       0 2234.22      26 2224.59    35.3 2218.74    53.9 2216.36    80.8 2204.11
   128.3 2187.09   151.5 2173.95   157.7 2169.17   165.5 2159.96   174.7  2154.9
   343.6 2156.28   365.3 2150.42   388.6 2149.47  394.112150.483   402.5 2153.87
   416.4 2154.62   585.9 2155.81   746.5 2159.47     793 2161.33   806.9  2164.3
   828.3 2163.91   834.8 2169.42   854.6 2181.03   921.7 2233.54   939.2 2245.47
  1002.1 2281.26  1029.3 2300.13  1039.3 2302.69  1090.4 2333.78  1160.5 2371.75
#Mann= 8 ,-1,0
       0      .1       0     280     .05       0   365.3    .045       0
  394.11     .05       0     400      .1       0     470     .05       0
     740     .06       0     970      .1       0
Bank Sta=365.3,394.11
XS Rating Curve= 0 ,0
Exp/Cntr(USF)=0,0
Exp/Cntr=0.3,0.1