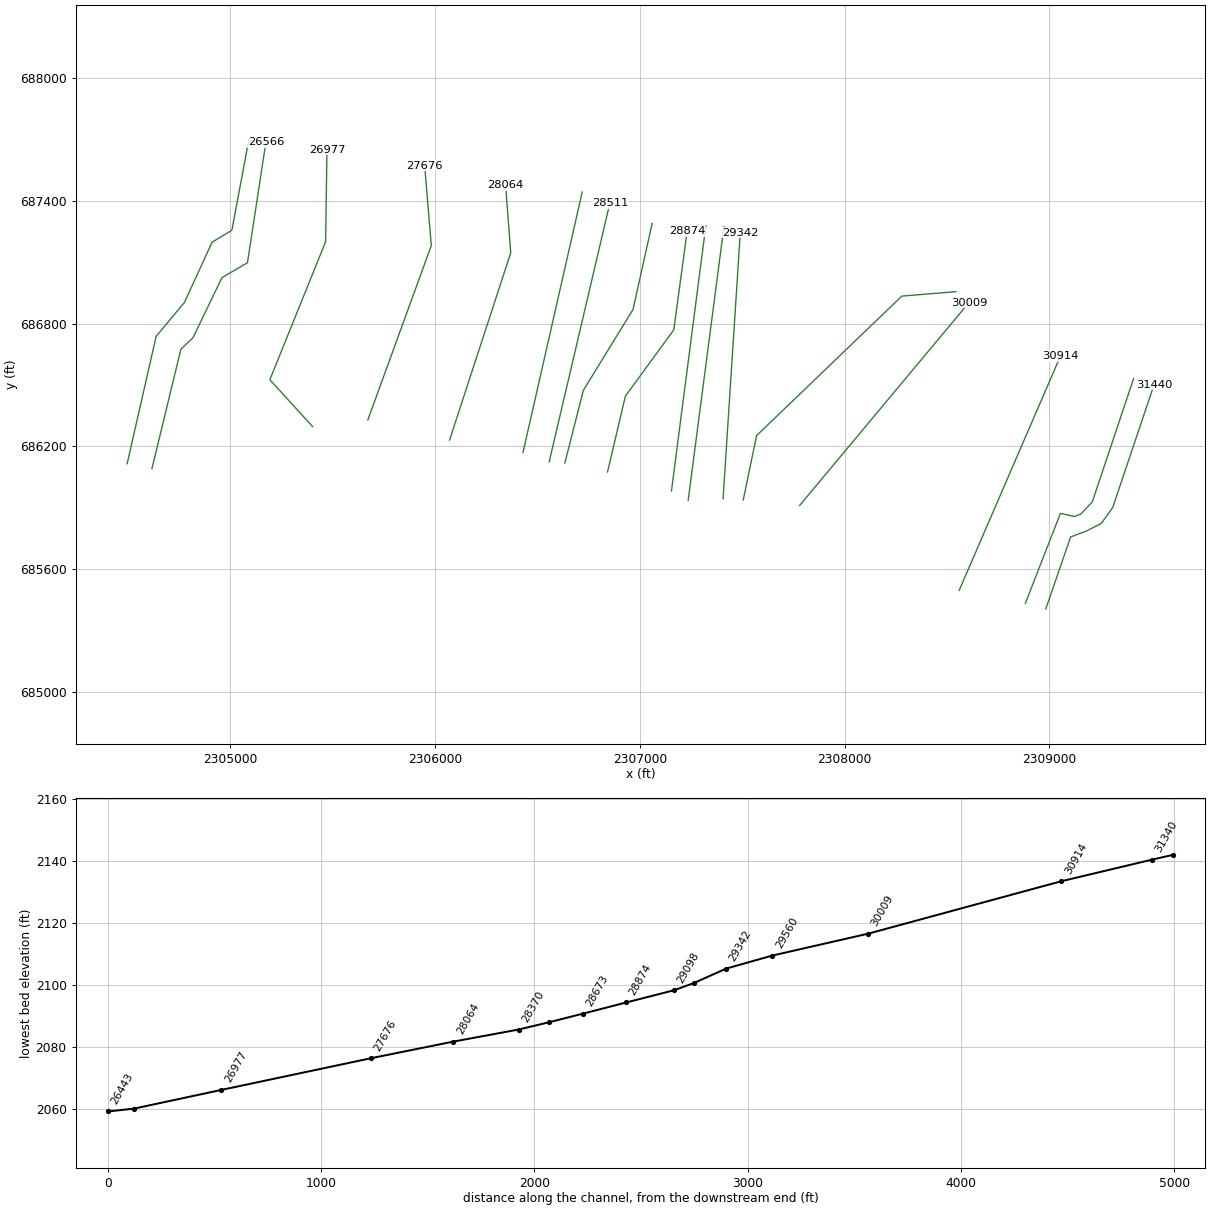
HEC-RAS study CHENOWTHCK.prj: CHENOWTHCK

--- CHENOWTHCK.g01 (geometry) --- (continued)

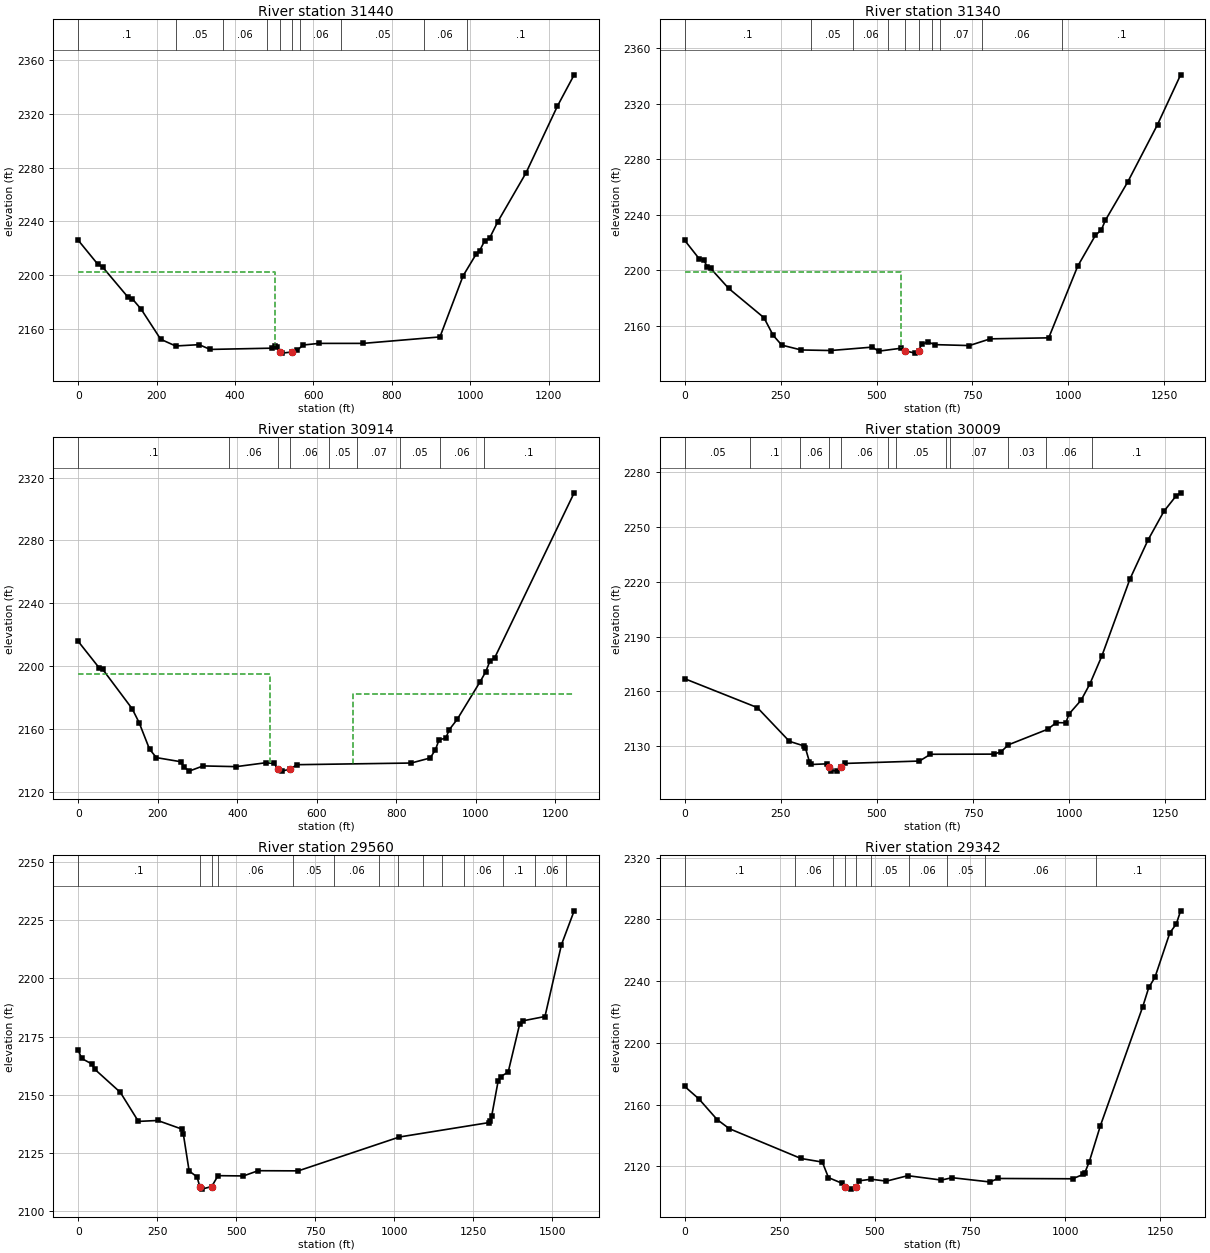
Type RM Length L Ch R = 1 ,31440   ,98.5,100.7,104
BEGIN DESCRIPTION:
Structure XS 3 Disconnected without IFA
END DESCRIPTION:
XS GIS Cut Line= 6
2308982.95944756 685406.362957472309104.29755328685757.932340716
 2309178.9671568685785.9334420362309253.63676032685823.268243797
2309309.63896296685901.0490807982309511.86913917686501.517142448
#Sta/Elev= 30
       0 2225.93    49.5 2208.23    62.2    2206   125.7 2183.98   138.3 2182.23
   160.5 2174.61   210.3 2152.23   248.4 2147.22   308.3  2148.2   336.6 2144.66
   493.3 2145.59   502.2  2146.9   506.7 2146.52  514.272142.675   520.1  2141.9
     544  2142.7   558.1 2143.92   573.5 2147.93     614 2149.15   726.8 2149.16
   922.5 2153.96   981.5 2199.47  1015.2 2215.82  1023.7 2218.17  1036.4 2225.44
  1049.1 2227.54  1070.2 2239.85  1141.9 2276.06  1222.1 2325.84  1264.7  2349.1
#Mann= 10 ,-1,0
       0      .1       0     250     .05       0     370     .06       0
  481.67     .05       0  514.27    .045       0     544     .05       0
  565.15     .06       0  671.08     .05       0  881.08     .06       0
  991.08      .1       0
#XS Ineff= 2 , 0
          502.38 2202.59
Permanent Ineff=
       F       F
Bank Sta=514.27,544
XS Rating Curve= 0 ,0
Exp/Cntr(USF)=0,0
Exp/Cntr=0.3,0.1

Type RM Length L Ch R = 1 ,31340   ,414.5,425.2,427.7
BEGIN DESCRIPTION:
Structure XS 2 Disconnected without IFA
END DESCRIPTION:
XS GIS Cut Line= 6
 2308883.3999762685434.364058791 2309054.5178176685873.047979478
2309122.96495416685857.4918120772309154.07728896685869.936745998
 2309210.0794916685929.050182119 2309412.3096678686532.629477249
#Sta/Elev= 30
       0 2221.56    37.4 2208.43    50.3  2207.1    58.8 2202.52    67.4 2201.42
   114.7 2186.93   206.6 2165.84   230.6 2153.15     253  2146.1   303.6  2142.6
   380.9  2142.2     489 2144.65   505.4 2141.72   563.3 2143.82   574.6 2141.94
   600.9 2140.32  609.962142.004   617.6 2146.64   634.1 2148.34   651.9 2146.44
   742.1 2145.77   796.4  2150.6   948.9 2151.33  1024.5 2202.98  1070.7 2225.23
  1086.1 2229.04  1096.3 2235.87  1154.7 2263.52  1232.5 2304.91  1292.7 2340.75
#Mann= 10 ,-1,0
       0      .1       0     330     .05       0     440     .06       0
  530.88     .07       0   574.6    .045       0  609.96     .07       0
  644.58     .06       0  666.01     .07       0  776.01     .06       0
  984.01      .1       0
#XS Ineff= 2 , 0
          563.03 2198.71
Permanent Ineff=
       F       F
Bank Sta=574.6,609.96
XS Rating Curve= 0 ,0
Exp/Cntr(USF)=0,0
Exp/Cntr=0.3,0.1

Type RM Length L Ch R = 1 ,30914   ,908.7,905.8,899.5
BEGIN DESCRIPTION:
Structure XS 1 Disconnected without IFA
END DESCRIPTION:
XS GIS Cut Line= 2
2308559.83169427685496.588728392 2309054.5178176 686641.52264905
#Sta/Elev= 30
       0 2215.84    52.9 2198.95    61.6 2198.05   135.7 2173.01   153.2 2164.19
   179.3 2147.35   196.7 2141.95   257.7 2139.35   266.4 2135.84   279.5 2133.42
   314.1 2136.68   397.2 2136.22   471.2 2138.68     493 2138.22   501.7 2134.78
   511.9 2133.37  533.842134.697   549.7 2137.46   837.5 2138.52   885.2 2141.73
   898.3 2146.96   907.4 2153.27   924.4 2154.35   933.1 2159.69   953.1 2166.29
  1010.9 2190.27  1024.6  2196.4  1035.2 2203.16  1047.4 2205.43  1247.2 2310.26
#Mann= 9 ,-1,0
       0      .1       0     380     .06       0   501.7    .045       0
  533.84     .06       0     630     .05       0     700     .07       0
     810     .05       0     910     .06       0    1020      .1       0
#XS Ineff= 2 , 0
          482.17 2194.83  689.92         2182.45
Permanent Ineff=
       F       F
Bank Sta=501.7,533.84
XS Rating Curve= 0 ,0
Exp/Cntr(USF)=0,0
Exp/Cntr=0.3,0.1

Type RM Length L Ch R = 1 ,30009   ,451.2,449.1,443.1
XS GIS Cut Line= 2
2307780.87216787685912.0628473182308607.46467885686902.461801022
#Sta/Elev= 30
       0 2166.98     189  2151.2   272.4 2132.77   309.8 2130.29   314.1 2129.08
   324.5  2121.6   329.7 2120.12   369.5 2120.47   376.6 2118.59   381.8 2116.83
   397.4 2116.49   407.8 2118.49   418.3  2120.7   610.7    2122   639.3  2125.7
     804 2125.78   822.9 2127.03   841.7 2130.84   944.5 2139.39   966.5 2142.99
   991.4  2142.9   999.9 2147.74  1031.2 2155.26  1053.9 2164.09  1085.2 2179.44
  1158.1 2221.39    1205 2242.68  1246.7 2258.48  1277.9 2266.76    1290 2268.53
#Mann= 12 ,-1,0
       0     .05       0     170      .1       0     300     .06       0
   376.6    .045       0   407.8     .06       0     530      .1       0
     550     .05       0     680      .1       0     690     .07       0
     840     .03       0     940     .06       0    1060      .1       0
Bank Sta=376.6,407.8
XS Rating Curve= 0 ,0
Exp/Cntr(USF)=0,0
Exp/Cntr=0.3,0.1

Type RM Length L Ch R = 1 ,29560   ,203.7,217.3,229.5
BEGIN DESCRIPTION:
Structure XS 4
END DESCRIPTION:
XS GIS Cut Line= 4
2307505.06842645685938.7020175622307570.40432953686252.936599047
2308279.76556298686934.2967311782308544.22040878686956.075365539
#Sta/Elev= 30
       0 2169.29    10.7 2165.64    43.4 2163.24    51.6 2161.08   133.3 2151.06
   190.5 2138.57   251.6 2138.96   327.1 2135.31   332.9 2133.05   351.1 2117.26
   376.1 2114.71   384.8 2110.55   390.6 2109.45  422.492110.545   442.6 2115.24
   523.1 2115.12   569.6 2117.37   696.6  2117.3  1016.7 2131.86  1299.6 2138.04
    1305 2138.76    1309 2140.99    1329 2155.72  1337.1  2157.8  1361.1 2159.78
  1397.3 2180.34  1409.3 2181.84  1477.5 2183.66  1529.7 2214.53  1569.9 2229.09
#Mann= 14 ,-1,0
       0      .1       0   384.8    .045       0  422.49      .1       0
  440.96     .06       0  680.96     .05       0  810.96     .06       0
  950.96     .08       0 1010.96     .07       0 1090.96     .08       0
 1150.96     .07       0 1220.96     .06       0 1344.54      .1       0
 1444.54     .06       0 1544.54     .08       0
Bank Sta=384.8,422.49
XS Rating Curve= 0 ,0
Exp/Cntr(USF)=0,0
Exp/Cntr=0.3,0.1

Type RM Length L Ch R = 1 ,29342   ,147.6,150.3,148.7
XS GIS Cut Line= 2
2307406.63997964685944.187398703 2307490.8194378687244.538502253
#Sta/Elev= 30
       0 2171.79    37.1 2163.77    85.2 2150.34   117.2 2144.43   305.6  2125.1
   361.7 2122.77   377.8  2112.7   413.9 2108.98   421.9 2106.37   437.9 2105.24
   451.12106.325   457.9 2110.61     490 2111.66   530.1 2110.41   586.2 2113.96
   674.4 2111.11   702.6 2112.65   802.7 2109.87   822.7 2112.14  1019.1 2111.95
  1047.2 2114.78  1051.2 2115.71  1063.2 2123.08  1092.3 2146.35  1203.5  2223.4
  1219.5 2235.96  1235.6 2242.46  1274.8 2271.33  1291.7 2277.06  1303.1  2285.6
#Mann= 10 ,-1,0
       0      .1       0     290     .06       0     390      .1       0
   421.9    .045       0   451.1      .1       0     490     .05       0
     590     .06       0     690     .05       0     790     .06       0
    1080      .1       0
Bank Sta=421.9,451.1
XS Rating Curve= 0 ,0
Exp/Cntr(USF)=0,0
Exp/Cntr=0.3,0.1

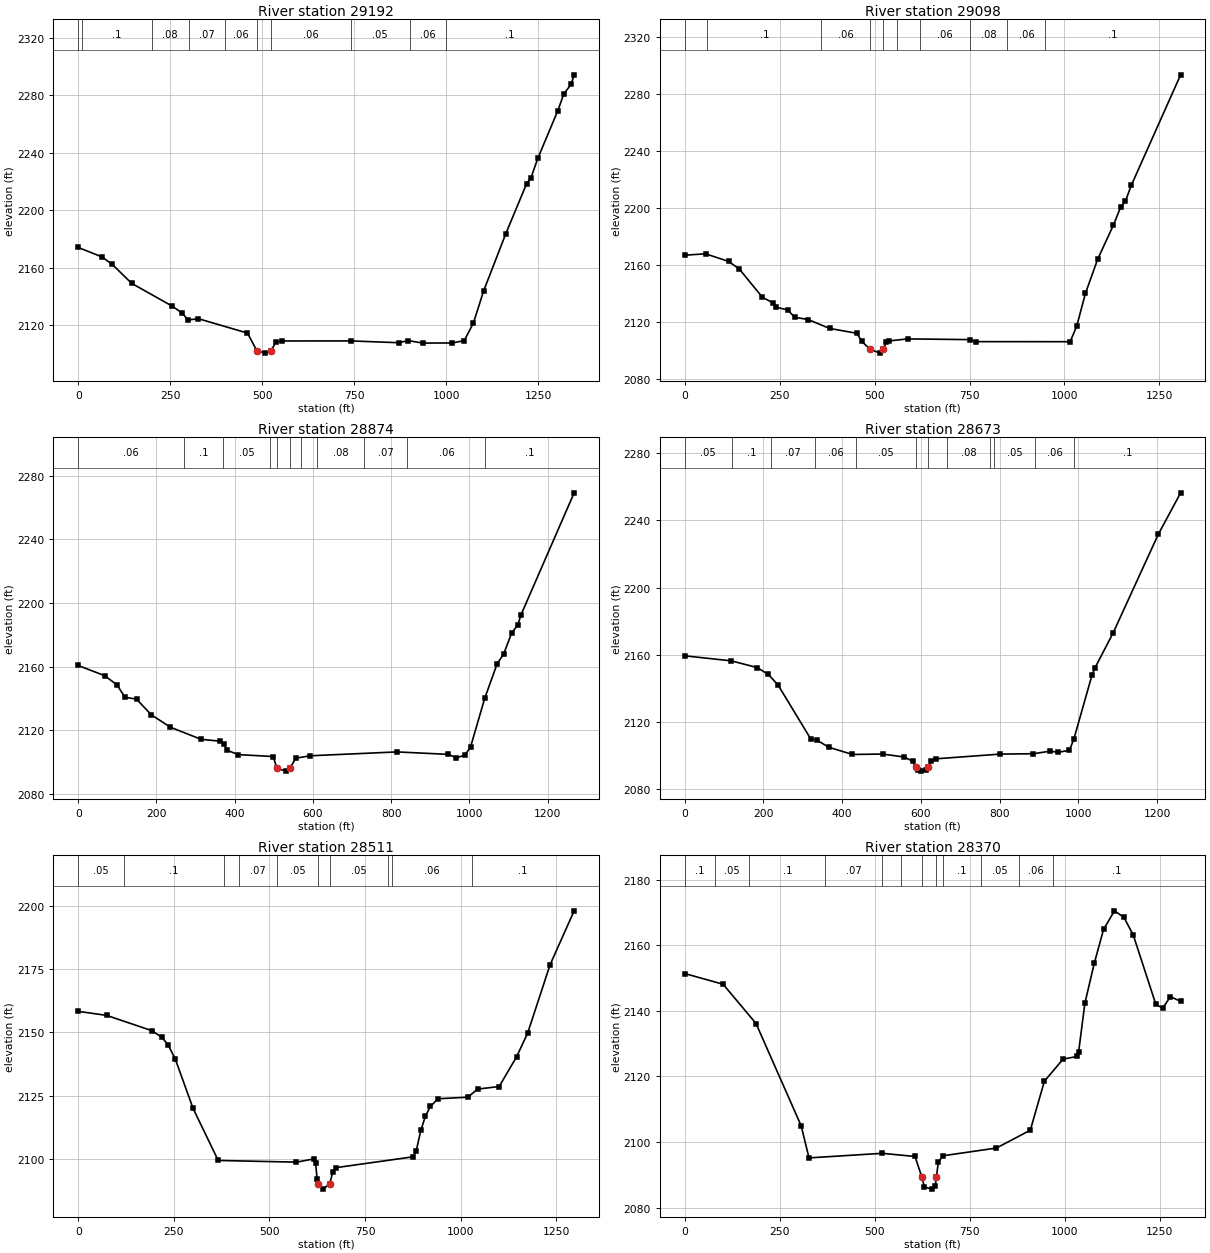
Type RM Length L Ch R = 1 ,29192   ,96.6,93.5,94.8
BEGIN DESCRIPTION:
Structure XS 3
END DESCRIPTION:
XS GIS Cut Line= 2
2307236.25474253 685937.242849062307410.89761147687273.147391958
#Sta/Elev= 30
       0 2174.15    64.1 2167.61    92.7  2162.3   145.2 2149.17   255.3 2133.31
   282.3 2128.52   298.5 2123.69   326.7 2124.55   459.8 2114.56   485.1 2102.37
   508.2 2100.61   523.82102.263   536.5 2108.12   552.6 2109.07     740 2109.11
   871.3 2107.85   895.7 2109.35   935.8 2107.62  1016.6 2107.68  1048.8 2109.33
  1073.7 2121.63  1101.2 2143.78  1161.7 2183.79  1218.2 2218.56  1230.3 2222.82
  1248.5 2236.12  1302.9 2269.29  1319.1 2280.92  1339.2 2287.75  1347.3 2294.27
#Mann= 10 ,-1,0
       0     .06       0      10      .1       0     200     .08       0
     300     .07       0     400     .06       0   485.1    .045       0
   523.8     .06       0     740     .05       0     900     .06       0
    1000      .1       0
Bank Sta=485.1,523.8
XS Rating Curve= 0 ,0
Exp/Cntr(USF)=0,0
Exp/Cntr=0.3,0.1

Type RM Length L Ch R = 1 ,29098   ,231.6,223.9,214.8
BEGIN DESCRIPTION:
Structure XS 2
END DESCRIPTION:
XS GIS Cut Line= 2
2307154.60353109685982.604633199 2307322.4421324687277.683570372
#Sta/Elev= 30
       0 2166.97      55 2167.96   115.5 2162.62   143.8 2157.31   204.3 2137.57
   232.5 2133.52   240.6 2130.54   271.5 2128.56   289.4 2123.46   325.3 2121.82
   381.7 2115.59   453.6  2112.2   466.4  2106.5  488.842100.855   514.8 2098.28
   522.9 2100.85     531 2105.81     539 2106.86   587.4 2108.26     750 2107.76
   765.8 2106.34    1015  2106.3  1032.1    2117  1055.3 2140.25  1087.6 2164.23
  1128.5 2187.83  1148.1 2200.75  1160.2 2204.68  1176.3 2216.16  1305.9 2293.51
#Mann= 10 ,-1,0
       0     .06       0      60      .1       0     360     .06       0
  488.84    .045       0   522.9     .06       0     560     .05       0
     620     .06       0     750     .08       0     850     .06       0
     950      .1       0
Bank Sta=488.84,522.9
XS Rating Curve= 0 ,0
Exp/Cntr(USF)=0,0
Exp/Cntr=0.3,0.1

Type RM Length L Ch R = 1 ,28874   ,200.2,201.5,202.7
BEGIN DESCRIPTION:
Structure XS 1
END DESCRIPTION:
XS GIS Cut Line= 4
2306842.37569519686075.5962906842306929.49023264 686445.83307481
2307165.94397712686769.401356736 2307231.2798802687251.642546144
#Sta/Elev= 30
       0 2160.71    67.4 2154.33    99.3 2148.53   119.2 2140.78   149.2 2139.57
   186.5  2129.8   235.7 2121.93   313.9 2114.35   363.2 2113.15   371.5 2111.63
   380.3 2107.48   409.3 2104.72   498.4 2103.53   507.92096.131   530.6 2094.35
   540.8 2096.01   556.4 2102.47   592.6 2103.99   814.9 2106.42   946.4 2104.88
   966.6 2102.76   988.4 2104.37  1002.9 2109.49  1039.2 2140.12  1070.8  2161.7
  1087.7 2167.99  1107.8    2181  1123.8 2186.27  1132.1 2192.63  1267.8 2269.19
#Mann= 11 ,-1,0
       0     .06       0     270      .1       0     370     .05       0
  490.35     .06       0   507.9    .045       0   540.8     .06       0
  570.35     .07       0  610.35     .08       0  730.35     .07       0
  841.11     .06       0 1041.11      .1       0
Bank Sta=507.9,540.8
XS Rating Curve= 0 ,0
Exp/Cntr(USF)=0,0
Exp/Cntr=0.3,0.1

Type RM Length L Ch R = 1 ,28673   ,157.5,162.3,167.3
BEGIN DESCRIPTION:
Structure XS 4
END DESCRIPTION:
XS GIS Cut Line= 4
2306633.92305203686119.1535594052306724.14882295686473.834176131
 2306966.8250344686868.960828097 2307060.1620388687288.977347905
#Sta/Elev= 30
       0 2159.38   118.7 2156.36   183.7 2152.41   212.6 2148.33   237.4 2141.93
   319.9 2110.06   336.4 2109.16     366 2104.99   426.2 2100.69   503.6 2100.94
   557.7 2099.15     580 2096.58   586.5 2093.08   592.4 2091.21   601.1 2090.78
     614 2091.25   618.2 2093.11   625.9 2096.88   637.5 2098.09   801.7 2100.91
   886.1 2101.13   928.2 2102.66   949.4 2101.97   977.4 2103.21   988.6 2109.76
  1034.8 2147.95  1042.2 2152.15    1088 2172.78  1203.1 2231.61  1259.9 2256.33
#Mann= 12 ,-1,0
       0     .05       0     120      .1       0     220     .07       0
     330     .06       0  435.98     .05       0   586.5    .045       0
   618.2     .06       0  665.98     .08       0  775.98     .06       0
  785.98     .05       0  889.68     .06       0  989.68      .1       0
Bank Sta=586.5,618.2
XS Rating Curve= 0 ,0
Exp/Cntr(USF)=0,0
Exp/Cntr=0.3,0.1

Type RM Length L Ch R = 1 ,28511   ,139.8,140.5,140.9
BEGIN DESCRIPTION:
Structure XS 3
END DESCRIPTION:
XS GIS Cut Line= 2
 2306557.2111704686124.7935649332306853.46973622687387.608665226
#Sta/Elev= 30
       0 2158.32    74.4 2156.72   193.5 2150.63   218.2 2148.09   234.6 2145.19
   254.2 2139.31   300.3 2119.94   366.1  2099.3   570.9 2098.63   616.7 2099.92
   620.8 2098.37   624.9  2091.9  627.222090.037   641.3 2087.95   657.8 2090.17
     666 2094.75     675 2096.47   875.5 2100.73   883.7 2102.85   896.1 2111.22
     908 2116.76   920.7 2120.66   941.3 2123.72  1019.3 2124.34  1044.4 2127.55
    1101 2128.56  1146.7 2140.38  1175.5 2149.72  1234.1 2176.76  1297.1 2198.11
#Mann= 10 ,-1,0
       0     .05       0     120      .1       0     380     .06       0
     420     .07       0     520     .05       0  627.22    .045       0
   657.8     .05       0     810     .07       0     820     .06       0
    1030      .1       0
Bank Sta=627.22,657.8
XS Rating Curve= 0 ,0
Exp/Cntr(USF)=0,0
Exp/Cntr=0.3,0.1

Type RM Length L Ch R = 1 ,28370   ,305.7,306.1,304.1
BEGIN DESCRIPTION:
Structure XS 2
END DESCRIPTION:
XS GIS Cut Line= 2
2306429.30490511686170.0792966992306718.64961876687442.919482649
#Sta/Elev= 30
       0 2151.37   101.2  2148.1   187.8 2136.13   306.7 2104.92   327.2 2095.16
     520 2096.56   606.2 2095.59  624.512089.253   630.8 2086.33     650 2085.64
   659.5 2086.67662.38912089.261   667.7 2093.91     680 2095.81   820.5 2098.17
   909.7  2103.6   946.7 2118.53   995.9 2125.28  1032.8 2126.08  1036.9 2127.54
  1053.3  2142.3  1077.9 2154.44  1102.5 2164.83  1131.2 2170.49  1155.9 2168.52
  1180.5 2163.17    1240 2142.01  1258.1 2140.79  1278.4 2144.33  1305.3 2142.89
#Mann= 12 ,-1,0
       0      .1       0      80     .05       0     170      .1       0
     370     .07       0     520     .06       0     570     .05       0
  624.51    .045       0662.3891     .05       0     680      .1       0
     780     .05       0     880     .06       0     970      .1       0
Bank Sta=624.51,662.3891
XS Rating Curve= 0 ,0
Exp/Cntr(USF)=0,0
Exp/Cntr=0.3,0.1

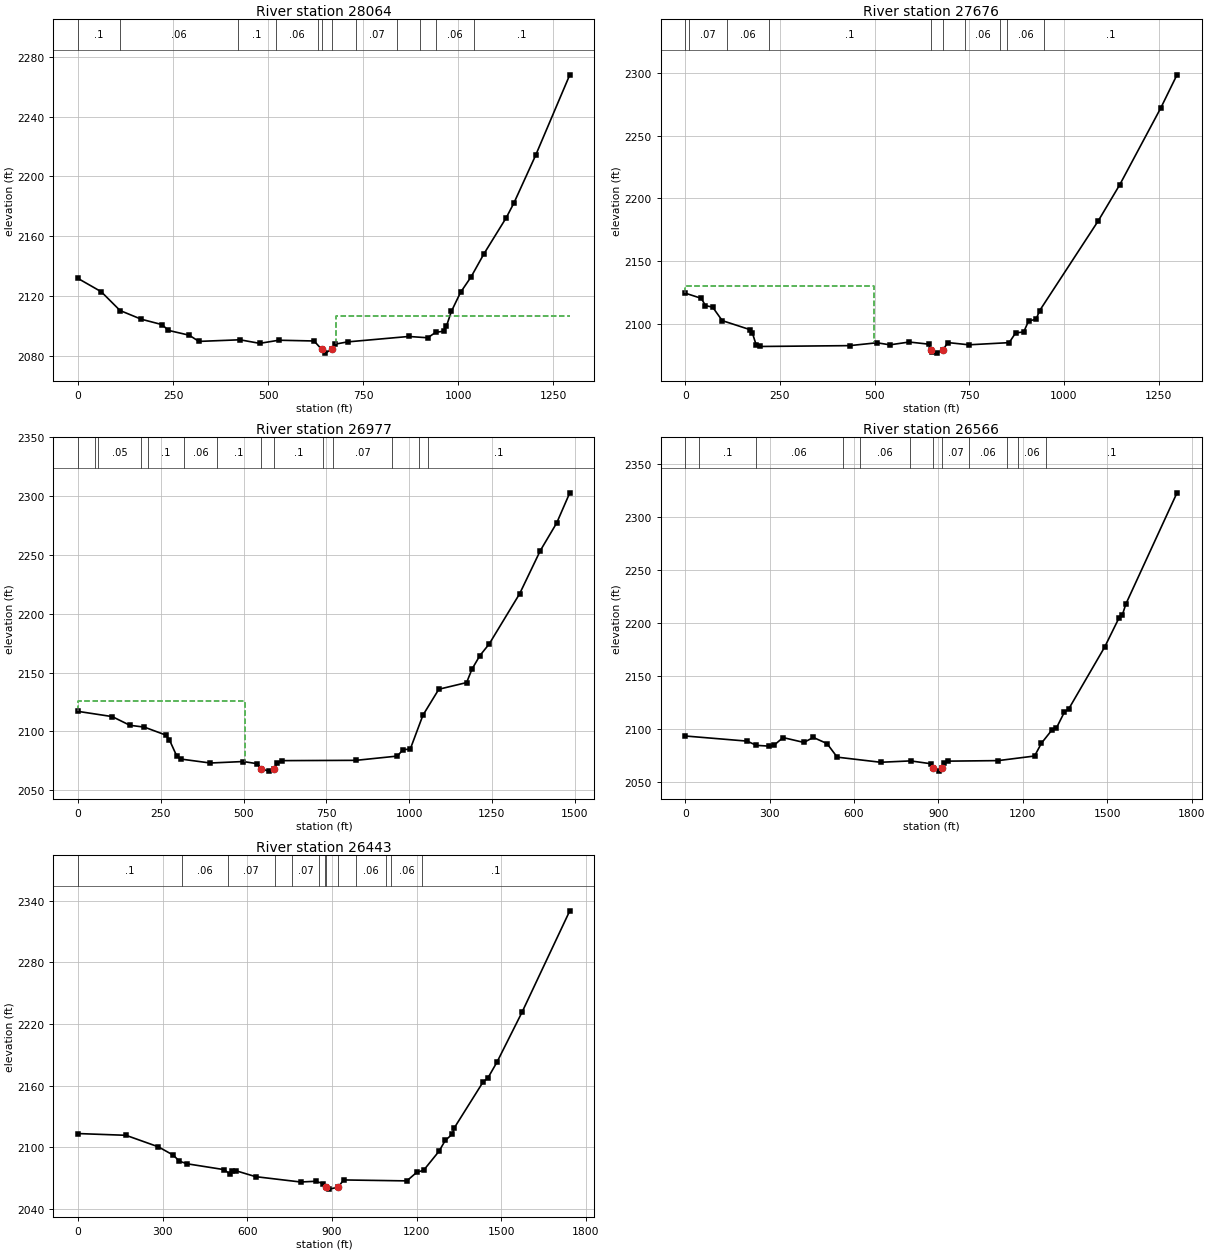
Type RM Length L Ch R = 1 ,28064   ,389.4,388.2,388
BEGIN DESCRIPTION:
Structure XS 1
END DESCRIPTION:
XS GIS Cut Line= 3
2306070.78979214686231.1579646872306369.46820623687145.860607822
2306344.57833839687475.651356708
#Sta/Elev= 30
       0 2131.71      61 2122.84   110.6 2110.25   166.2 2104.45   220.9 2100.83
   237.8 2096.96   292.5 2093.74   317.7  2089.6   425.9 2090.68   477.6  2088.3
   528.1 2090.39   620.7 2089.88   640.3  2084.4   650.1 2081.76     667 2084.33
   675.4 2087.73     709 2089.28   869.5  2092.9   919.5 2092.03   940.5 2095.68
   961.5 2096.41   968.8 2099.87   981.6 2109.62  1005.7 2122.35  1033.8 2132.87
  1067.2 2148.13    1126 2172.34  1146.1 2182.15  1203.1 2213.99    1293 2267.88
#Mann= 12 ,-1,0
       0      .1       0     110     .06       0     420      .1       0
     520     .06       0     630      .1       0   640.3    .045       0
     667      .1       0     730     .07       0     840     .08       0
     900     .05       0     940     .06       0 1042.23      .1       0
#XS Ineff= 2 , 0
                          679.17         2106.29
Permanent Ineff=
       F       F
Bank Sta=640.3,667
XS Rating Curve= 0 ,0
Exp/Cntr(USF)=0,0
Exp/Cntr=0.3,0.1

Type RM Length L Ch R = 1 ,27676   ,695.5,699.4,689
XS GIS Cut Line= 3
2305671.43643047686329.3658085622305981.43973443687181.181089365
2305949.10468487687571.874233623
#Sta/Elev= 30
       0 2124.24    42.4  2120.1    53.5 2114.23    72.2 2113.15    97.7 2102.32
   172.1 2095.02   177.6 2092.18   187.1 2083.14     197 2081.68   434.2 2082.36
   506.3 2084.64   540.4    2083   591.5 2085.23   642.6 2083.55  648.632079.237
   651.1 2077.09   663.8 2076.38   680.5 2079.05   693.6  2084.8     749 2083.02
   855.4 2084.75   872.4 2092.53   893.7 2093.27   906.5 2101.94   926.5 2103.46
   935.7 2110.23  1091.1 2182.19  1147.3 2210.73  1255.7 2272.02  1298.5 2298.44
#Mann= 10 ,-1,0
       0      .1       0      10     .07       0     110     .06       0
     220      .1       0  648.63    .045       0   680.5      .1       0
     740     .06       0     830     .05       0     850     .06       0
  946.47      .1       0
#XS Ineff= 2 , 0
          497.33 2130.17
Permanent Ineff=
       F       F
Bank Sta=648.63,680.5
XS Rating Curve= 0 ,0
Exp/Cntr(USF)=0,0
Exp/Cntr=0.3,0.1

Type RM Length L Ch R = 1 ,26977   ,410.7,410.1,409.3
BEGIN DESCRIPTION:
Structure XS 4
END DESCRIPTION:
XS GIS Cut Line= 4
2305401.67693158  686296.94675572305193.01272454686526.023765603
2305465.18342938687199.646260069  2305471.987697687648.727923047
#Sta/Elev= 30
       0 2117.02   103.2 2112.59   156.7 2105.18   200.5 2103.62   265.4 2096.85
   276.3  2092.7   297.9 2079.27   309.9  2076.5   399.6 2073.11   499.1 2074.37
   541.9  2072.5   553.2 2068.04   576.4 2066.21  591.312068.077   602.3 2073.16
   615.3 2075.13   840.1 2075.39   964.7 2079.01     982 2084.57  1003.5 2084.83
  1041.9 2113.76  1089.9 2135.83  1173.9 2141.51  1189.9 2152.85  1213.9 2164.43
    1242  2174.3    1334 2217.02  1396.4 2253.66    1446 2277.24  1485.5 2302.85
#Mann= 14 ,-1,0
       0     .05       0      50      .1       0      60     .05       0
     190     .06       0     210      .1       0  319.87     .06       0
  419.87      .1       0   553.2    .045       0  591.31      .1       0
  739.87     .05       0  769.87     .07       0  949.87      .1       0
 1029.87     .06       0 1056.39      .1       0
#XS Ineff= 2 , 0
          504.84 2125.52
Permanent Ineff=
       F       F
Bank Sta=553.2,591.31
XS Rating Curve= 0 ,0
Exp/Cntr(USF)=0,0
Exp/Cntr=0.3,0.1

Type RM Length L Ch R = 1 ,26566   ,123.5,123.2,124.4
BEGIN DESCRIPTION:
Structure XS 3
END DESCRIPTION:
XS GIS Cut Line= 6
2304616.83855668686091.2613818712304758.57252632686675.481890903
2304817.34026983686730.7927083262304959.07423948687024.631425887
2305083.52357868687097.226873755  2305173.403657687684.904308876
#Sta/Elev= 30
       0 2093.29   220.1 2088.45   253.1 2084.46   298.3 2083.74   315.7 2084.58
   347.7  2091.8   421.7 2087.23   455.3 2091.92   504.1 2086.13   540.1 2073.35
   694.6 2068.53   801.1 2069.82   872.6 2067.16   880.5 2062.71   903.3 2060.18
   912.1  2062.7   920.9 2067.69     934 2069.59  1112.2 2070.09  1241.8 2074.42
  1266.3 2086.57  1303.2 2098.86  1319.4 2100.83  1347.7 2115.76  1362.9 2118.68
    1491 2177.16  1541.9 2204.59  1554.1 2207.69  1566.2 2217.63    1748 2322.44
#Mann= 12 ,-1,0
       0     .06       0      50      .1       0     250     .06       0
     560     .07       0  621.17     .06       0  799.41      .1       0
   880.5    .045       0   912.1     .07       0 1008.26     .06       0
 1142.24     .07       0 1183.51     .06       0 1283.51      .1       0
Bank Sta=880.5,912.1
XS Rating Curve= 0 ,0
Exp/Cntr(USF)=0,0
Exp/Cntr=0.3,0.1

Type RM Length L Ch R = 1 ,26443   ,746.4,750.6,752.9
BEGIN DESCRIPTION:
Structure XS 2
END DESCRIPTION:
XS GIS Cut Line= 6
2304495.84614356686115.4598644932304637.58011321686737.706560504
2304775.85715677686903.6390127732304910.67727424687197.477730334
2305007.47120473687256.2454738462305090.43743086687698.732013231
#Sta/Elev= 30
       0 2113.35     170 2111.65   284.8 2100.42   338.2 2092.23   359.2 2086.43
   387.4 2083.89   518.7 2078.19   539.2 2073.59   547.4 2076.98   559.7 2077.16
   629.4  2071.4   788.8  2066.2   842.1  2066.9   869.1 2064.65   879.32061.259
   890.3 2059.26     922 2061.14   941.3  2068.2  1165.2 2067.28  1200.6 2075.64
    1225 2077.65    1279 2095.99  1301.7 2106.73  1326.1 2112.68  1334.2 2119.18
    1436 2163.75  1452.3 2167.31  1484.8 2182.88  1573.4 2231.36  1742.8 2330.14
#Mann= 13 ,-1,0
       0      .1       0     370     .06       0     530     .07       0
  698.18     .06       0  758.18     .07       0  854.74     .06       0
  874.74     .07       0   879.3    .045       0     922     .07       0
  984.74     .06       0 1089.85      .1       0 1109.85     .06       0
 1219.35      .1       0
Bank Sta=879.3,922
XS Rating Curve= 0 ,0
Exp/Cntr(USF)=0,0
Exp/Cntr=0.3,0.1