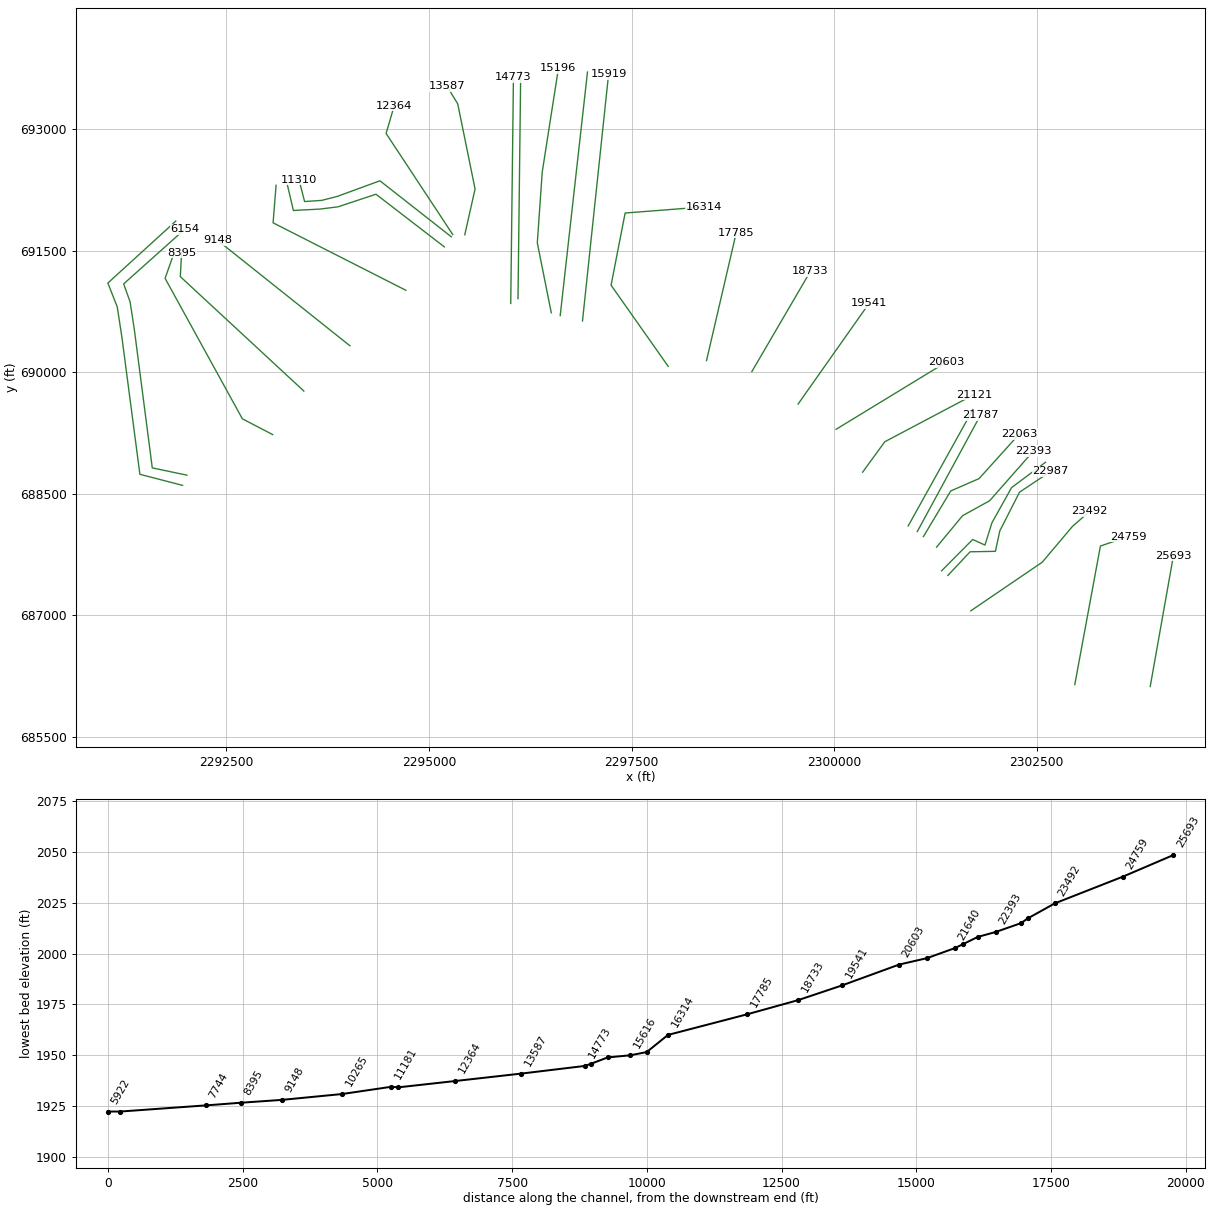
HEC-RAS study CHENOWTHCK.prj: CHENOWTHCK

--- CHENOWTHCK.g01 (geometry) --- (continued)

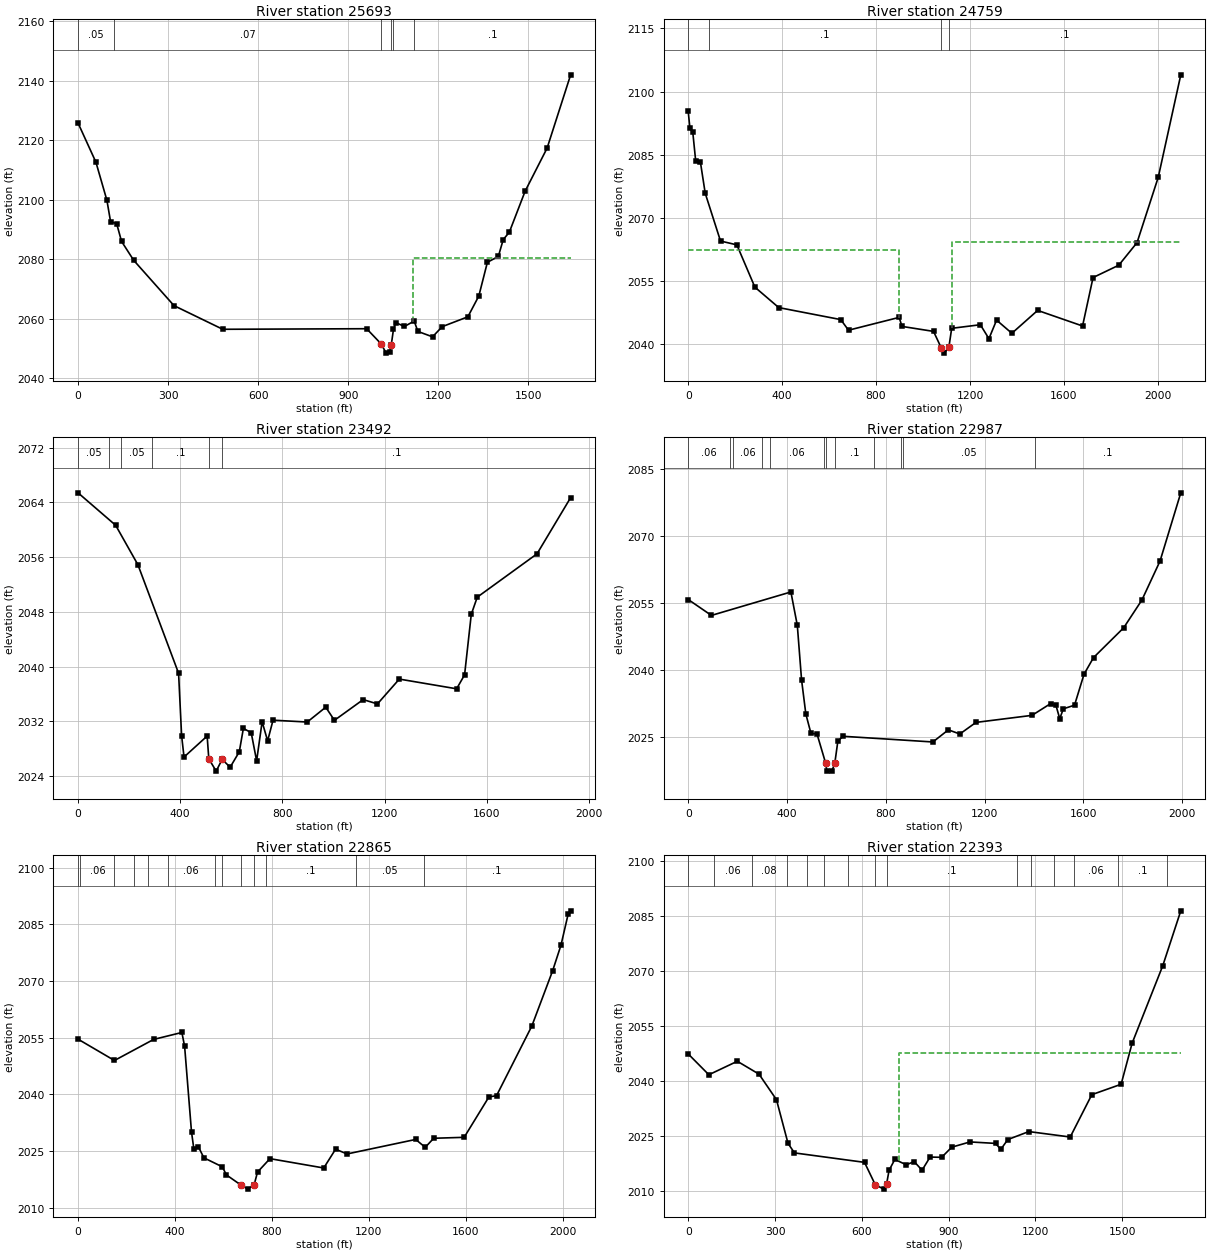
Type RM Length L Ch R = 1 ,25693   ,933.2,933.4,933.2
BEGIN DESCRIPTION:
Structure XS 1
END DESCRIPTION:
XS GIS Cut Line= 2
2303900.89399507686122.490159388 2304187.7563947687738.286532823
#Sta/Elev= 30
       0 2125.81    59.6 2112.64    96.2 2099.83   108.4 2092.65   128.7    2092
   144.9 2086.05   185.5 2079.68   319.6 2064.47   482.1 2056.52   961.5 2056.71
  1010.2 2051.57  1026.4 2048.51  1038.7 2048.95 1043.692051.399  1050.9 2056.55
    1059 2058.74  1087.4 2057.47  1119.9 2059.28  1132.1  2055.8  1180.9 2053.99
  1213.4 2057.41  1298.7 2060.71  1335.2  2067.7  1363.7 2079.02  1400.2 2080.99
  1416.5 2086.65  1436.8 2089.13  1489.6 2102.94  1562.7 2117.39  1641.1    2142
#Mann= 6 ,-1,0
       0     .05       0     120     .07       0  1010.2    .045       0
 1043.69      .1       0    1050     .07       0    1120      .1       0
#XS Ineff= 2 , 0
                         1116.39         2080.55
Permanent Ineff=
       F       F
Bank Sta=1010.2,1043.69
XS Rating Curve= 0 ,0
Exp/Cntr(USF)=0,0
Exp/Cntr=0.3,0.1

Type RM Length L Ch R = 1 ,24759   ,1282.6,1266.9,1247.7
XS GIS Cut Line= 3
2302970.05477994686145.9074981342303286.18885301 687855.37322655
2303625.74026481687972.459920278
#Sta/Elev= 30
       0 2095.32     7.4  2091.3    19.6 2090.31    31.8  2083.6    52.1 2083.23
    72.5 2075.86   137.6 2064.52   207.2 2063.61     284 2053.57   385.6 2048.72
   649.6 2045.87   682.7 2043.35   898.2 2046.39   910.5 2044.25  1044.7 2043.07
  1077.2  2039.2  1089.4 2037.91    1110 2039.27    1122  2043.8  1244.1 2044.65
  1280.6 2041.34  1313.2 2045.74  1378.3 2042.62  1488.1 2048.05  1679.3 2044.35
    1724 2055.85  1833.6 2058.78  1911.3 2064.14  2001.7 2079.67  2097.6 2103.97
#Mann= 4 ,-1,0
       0     .06       0      90      .1       0  1077.2    .045       0
    1110      .1       0
#XS Ineff= 2 , 0
          898.92 2062.28 1122.31         2064.27
Permanent Ineff=
       F       F
Bank Sta=1077.2,1110
XS Rating Curve= 0 ,0
Exp/Cntr(USF)=0,0
Exp/Cntr=0.3,0.1

Type RM Length L Ch R = 1 ,23492   ,512.8,505,493.9
BEGIN DESCRIPTION:
Structure XS 4
END DESCRIPTION:
XS GIS Cut Line= 4
2301686.37741577687055.7582880562302568.17455311687655.848291562
2302940.00897099688096.4859581752303154.39607055688284.618314656
#Sta/Elev= 30
       0  2065.4   147.3 2060.65   234.4 2054.88   393.6 2039.01   405.4 2029.89
   414.9 2026.76   505.4 2029.83   511.9  2026.5   540.7  2024.7   564.2 2026.42
   595.4 2025.27   631.2 2027.52   647.2 2030.95   677.9 2030.32   699.1  2026.2
   720.6 2031.92   742.2 2029.13   763.3 2032.15   897.3 2031.88   969.7 2034.05
  1003.7 2032.13  1116.2 2035.16  1172.1 2034.53  1257.7 2038.16    1482 2036.74
  1513.2 2038.78  1539.4 2047.63  1562.8 2050.14  1796.8 2056.48  1928.4  2064.7
#Mann= 6 ,-1,0
       0     .05       0     120      .1       0     170     .05       0
     290      .1       0   511.9    .045       0   564.2      .1       0
Bank Sta=511.9,564.2
XS Rating Curve= 0 ,0
Exp/Cntr(USF)=0,0
Exp/Cntr=0.3,0.1

Type RM Length L Ch R = 1 ,22987   ,121.7,122.2,127.3
BEGIN DESCRIPTION:
Structure XS 3
END DESCRIPTION:
XS GIS Cut Line= 6
2301403.64345833687492.7567131772301678.32401139687784.604800813
2301990.20088936687790.3273123352302044.56474882688042.117819315
2302287.77148852688519.9475314252302674.04101627688777.460549928
#Sta/Elev= 30
       0 2055.75      94 2052.18   415.7 2057.44   441.7 2049.94   458.9 2037.71
   476.2 2030.06     497  2025.7   521.4 2025.59  556.132019.078   561.6 2017.27
   581.6 2017.25   593.6  2019.1   605.6 2023.91   625.8 2025.07   990.4 2023.79
    1053 2026.51  1099.5 2025.58  1164.8 2028.18  1391.5 2029.76  1466.5 2032.38
  1488.6 2031.99  1503.9 2029.01  1518.4 2031.23  1563.7 2032.04  1602.2    2039
  1640.6 2042.72  1762.6  2049.4  1836.5 2055.64  1909.9 2064.39  1993.8 2079.68
#Mann= 12 ,-1,0
       0     .06       0     170     .05       0     180     .06       0
     300     .03       0     330     .06       0  550.78      .1       0
  556.13    .045       0   593.6      .1       0  752.79     .05       0
  860.14      .1       0  870.14     .05       0 1402.59      .1       0
Bank Sta=556.13,593.6
XS Rating Curve= 0 ,0
Exp/Cntr(USF)=0,0
Exp/Cntr=0.3,0.1

Type RM Length L Ch R = 1 ,22865   ,458.6,471.9,475.4
BEGIN DESCRIPTION:
Structure XS 2
END DESCRIPTION:
XS GIS Cut Line= 6
2301326.38955277  687549.98182842301709.79782477687936.251356153
2301861.44438011687867.5812178862301947.28205294688142.261770955
2302190.48879264688577.1726466482302608.23213376688889.049524612
#Sta/Elev= 30
       0 2054.62   150.2 2048.98   311.8 2054.55   428.4 2056.39   439.7 2052.72
   468.1  2030.1   477.9 2025.54   496.5 2026.16   519.2 2023.24     595 2020.87
   612.4 2018.71   671.3 2016.07   700.3 2014.96   726.5  2016.1   740.5 2019.47
   791.9 2023.02  1013.7 2020.55  1062.6 2025.52  1109.8 2024.26  1393.1  2028.1
  1432.4 2026.01  1467.4 2028.41  1593.1 2028.66  1695.2 2039.34  1726.7 2039.68
  1872.2 2058.08  1958.2 2072.73  1992.5 2079.47  2022.4 2087.77  2032.4 2088.56
#Mann= 13 ,-1,0
       0     .07       0      10     .06       0     150     .05       0
     230     .06       0     290     .03       0     370     .06       0
  564.25      .1       0  594.25     .06       0   671.3    .045       0
   726.5     .07       0   776.9      .1       0 1146.96     .05       0
 1426.61      .1       0
Bank Sta=671.3,726.5
XS Rating Curve= 0 ,0
Exp/Cntr(USF)=0,0
Exp/Cntr=0.3,0.1

Type RM Length L Ch R = 1 ,22393   ,332.1,330.5,329
BEGIN DESCRIPTION:
Structure XS 1
END DESCRIPTION:
XS GIS Cut Line= 4
2301264.07776064687842.147833342 2301585.1742405 688230.00694763
2301918.98741264 688414.398985572302459.44683418689027.979387681
#Sta/Elev= 30
       0  2047.4    71.4 2041.73   169.8  2045.4   244.8 2041.89   305.1 2034.94
   345.1 2023.03   367.4 2020.45   609.4 2017.88   646.4 2011.82   675.5 2010.59
  685.672011.977   694.3 2015.71   714.1 2018.67   753.7 2017.22   781.1 2018.08
   808.3 2015.74     836 2019.32     876 2019.25   910.9 2022.01   973.9 2023.44
  1062.2 2023.04  1080.5 2021.41  1104.5 2024.08  1177.2 2026.26  1320.4 2024.78
    1395 2036.31  1496.3 2039.14  1534.2  2050.3  1640.2 2071.41  1702.5 2086.36
#Mann= 15 ,-1,0
       0     .07       0      90     .06       0     220     .08       0
     340     .07       0     410     .05       0     470     .06       0
  553.53      .1       0   646.4    .045       0  685.67      .1       0
 1134.88     .05       0 1184.88     .06       0 1264.88     .05       0
 1334.88     .06       0 1484.88      .1       0 1654.88     .08       0
#XS Ineff= 2 , 0
                           729.1         2047.76
Permanent Ineff=
       F       F
Bank Sta=646.4,685.67
XS Rating Curve= 0 ,0
Exp/Cntr(USF)=0,0
Exp/Cntr=0.3,0.1

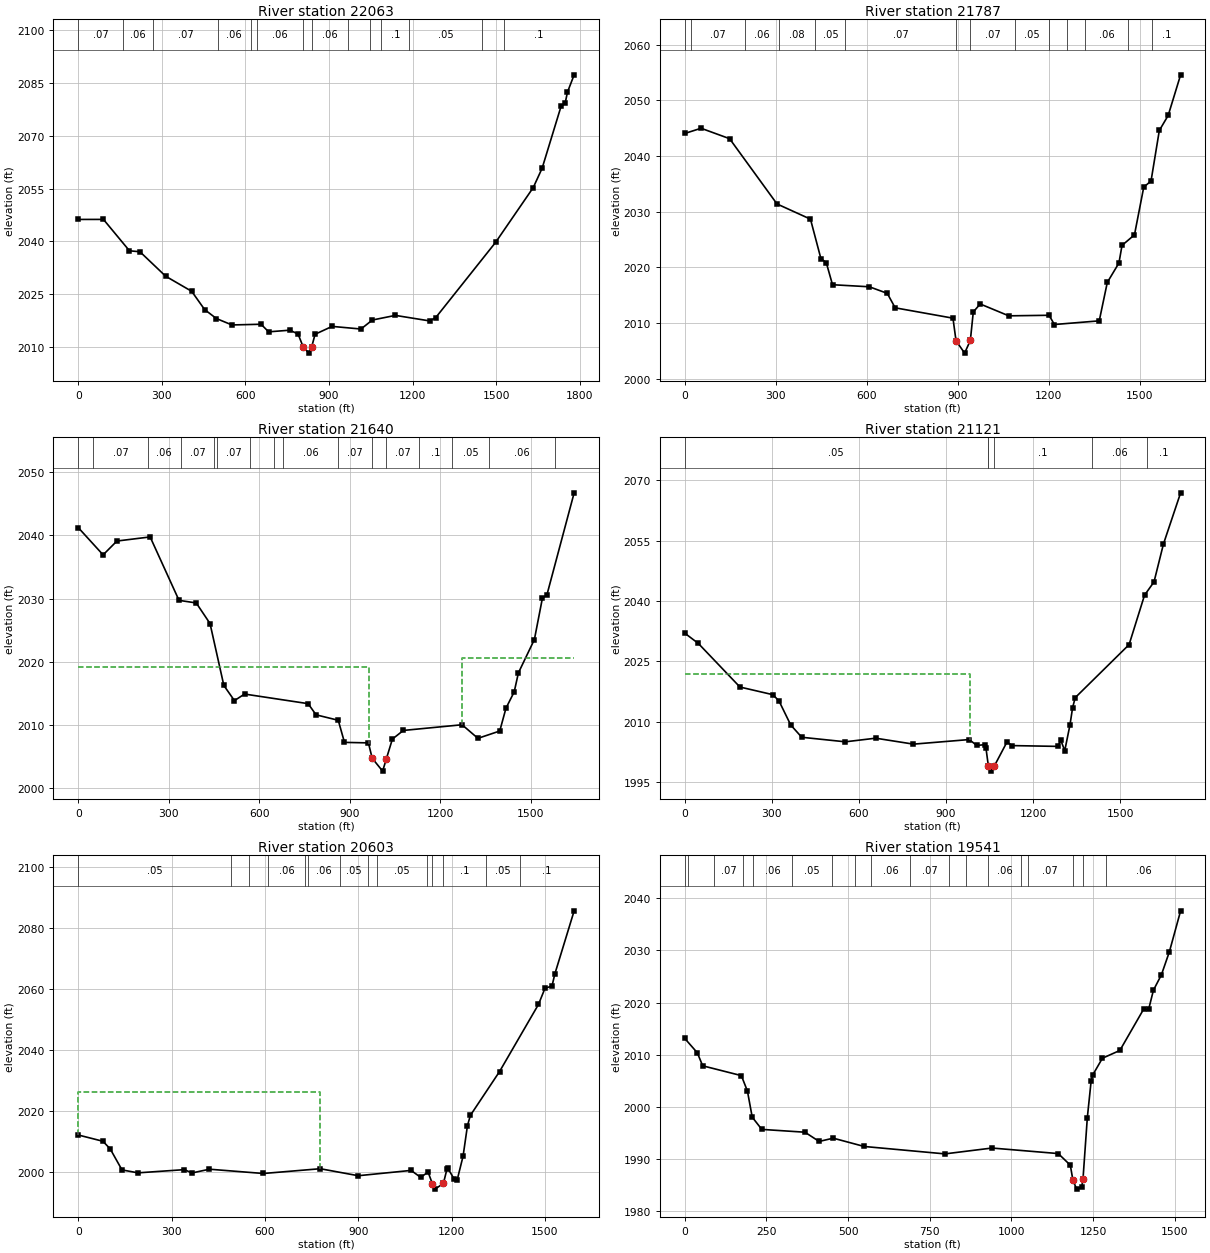
Type RM Length L Ch R = 1 ,22063   ,257.5,275.7,285.7
BEGIN DESCRIPTION:
Structure XS 4
END DESCRIPTION:
XS GIS Cut Line= 4
2301101.68001967687972.0151269742301438.93227938688535.207562151
2301788.64131685688687.8078694122302285.19665466689238.128094792
#Sta/Elev= 30
       0 2046.22    90.5 2046.23   183.9 2037.29   221.4 2037.03   313.7 2030.06
     407 2025.77   453.6 2020.56   495.6 2018.02   551.5 2016.19   655.9 2016.39
   683.2 2014.23   759.2  2014.7   788.7 2013.61   807.8 2009.79     828 2008.17
  837.012009.787   849.8 2013.54   910.9 2015.78  1014.4 2015.03  1055.2 2017.59
  1137.8 2018.91  1260.7 2017.34  1282.3 2018.25  1497.5 2039.71  1632.5  2055.3
  1664.3 2060.79  1732.5 2078.49  1746.7 2079.22  1755.2 2082.45  1779.2 2087.38
#Mann= 14 ,-1,0
       0     .07       0     160     .06       0     270     .07       0
     500     .06       0     620     .07       0     640     .06       0
   807.8    .045       0  837.01     .06       0  966.45     .07       0
    1048     .08       0    1088      .1       0    1188     .05       0
    1448     .06       0    1528      .1       0
Bank Sta=807.8,837.01
XS Rating Curve= 0 ,0
Exp/Cntr(USF)=0,0
Exp/Cntr=0.3,0.1

Type RM Length L Ch R = 1 ,21787   ,149.7,146.9,148.9
BEGIN DESCRIPTION:
Structure XS 3
END DESCRIPTION:
XS GIS Cut Line= 2
2301026.39185104688034.3175373792301806.12073554689470.862378786
#Sta/Elev= 30
       0 2044.04      54 2044.98     148 2043.11   304.3 2031.38   414.6 2028.65
   448.9 2021.57   466.6 2020.85   487.2 2016.87   608.6  2016.5   667.7 2015.32
   693.7 2012.72   884.2 2010.86   894.3  2006.8   922.6 2004.58   941.5 2006.86
   951.2 2011.98     974 2013.41  1068.2 2011.28  1201.1 2011.38  1218.4 2009.72
  1366.3 2010.38  1392.9 2017.29  1431.2 2020.77  1441.4 2023.94  1482.4 2025.83
    1513 2034.41    1537  2035.5  1564.3 2044.58  1593.5 2047.28  1634.5 2054.58
#Mann= 14 ,-1,0
       0     .06       0      20     .07       0     200     .06       0
     310     .08       0     430     .05       0     530     .07       0
   894.3    .045       0   941.5     .07       0    1090     .05       0
    1200     .06       0    1260     .07       0    1320     .06       0
    1460     .07       0    1540      .1       0
Bank Sta=894.3,941.5
XS Rating Curve= 0 ,0
Exp/Cntr(USF)=0,0
Exp/Cntr=0.3,0.1

Type RM Length L Ch R = 1 ,21640   ,533.4,519.6,508.2
BEGIN DESCRIPTION:
Structure XS 2
END DESCRIPTION:
XS GIS Cut Line= 2
2300913.80284114688103.3342985392301712.73687059689539.879139946
#Sta/Elev= 30
       0 2041.24    82.5 2036.92   128.3 2039.11   238.4 2039.76   334.1 2029.72
   391.2 2029.31   436.9 2026.05   482.7 2016.25   517.8 2013.85   551.3 2014.89
     762 2013.37   788.4  2011.6   861.9 2010.74   882.5 2007.24   961.9 2007.16
  974.382004.729    1009 2002.69  1020.8 2004.55  1041.4 2007.77  1077.7 2009.13
  1272.3 2010.03  1324.9 2007.88  1397.2 2009.04  1417.8 2012.65  1445.1 2015.24
    1459 2018.24    1512 2023.52  1538.4 2030.02  1553.7 2030.62  1643.8 2046.74
#Mann= 16 ,-1,0
       0     .06       0      50     .07       0     230     .06       0
     340     .07       0     450     .08       0     460     .07       0
     570     .06       0     650     .07       0     680     .06       0
     860     .07       0  974.38    .045       0  1020.8     .07       0
    1130      .1       0    1240     .05       0    1360     .06       0
    1580      .1       0
#XS Ineff= 2 , 0
          963.03 2019.22 1272.35          2020.6
Permanent Ineff=
       F       F
Bank Sta=974.38,1020.8
XS Rating Curve= 0 ,0
Exp/Cntr(USF)=0,0
Exp/Cntr=0.3,0.1

Type RM Length L Ch R = 1 ,21121   ,513.1,518,519.7
BEGIN DESCRIPTION:
Structure XS 1
END DESCRIPTION:
XS GIS Cut Line= 3
2300351.65509015 688767.287196112300625.06397399689142.429618126
2301725.05785549689724.218289558
#Sta/Elev= 30
       0 2032.04    46.9 2029.48   190.4 2018.63   304.3 2016.72   325.2 2015.13
   365.3  2009.2   403.3 2006.14   553.7 2005.01     658 2005.91   788.2 2004.43
   980.6 2005.57  1006.2  2004.1  1033.8  2004.3  1037.9 2003.48 1046.231999.015
    1056 1997.72  1066.4 1998.94  1110.3 2004.95  1128.4 2004.07  1285.4 2003.87
  1295.8 2005.39  1309.4  2002.8  1327.5 2009.25  1336.5 2013.52  1345.6    2016
  1531.1 2029.18  1584.3 2041.47  1616.9 2044.77  1649.4 2054.18  1708.6 2066.92
#Mann= 6 ,-1,0
       0     .05       0  1044.2      .1       0 1046.23    .045       0
  1066.4      .1       0  1404.2     .06       0  1594.2      .1       0
#XS Ineff= 2 , 0
          983.55 2021.88
Permanent Ineff=
       F       F
Bank Sta=1046.23,1066.4
XS Rating Curve= 0 ,0
Exp/Cntr(USF)=0,0
Exp/Cntr=0.3,0.1

Type RM Length L Ch R = 1 ,20603   ,1052.9,1061.3,1067.2
XS GIS Cut Line= 2
2300024.04896291689296.1608356762301385.00614745690126.012777467
#Sta/Elev= 30
       0 2012.27    79.4 2010.21   102.7 2007.73   140.7 2000.83   192.2 1999.87
   341.3 2000.92   365.6 1999.83   421.8 2001.06   595.1 1999.66   777.9 2001.22
   900.1 1998.93  1069.9 2000.67  1100.7 1998.39  1124.5 2000.14 1138.09 1996.36
  1146.8 1994.54  1173.8 1996.41  1185.3 2001.17  1188.3 2001.34  1208.6 1997.76
  1218.2 1997.62    1237 2005.33    1251 2015.28  1260.4 2018.68  1354.1 2033.02
  1479.3 2055.01  1500.2 2060.28  1522.8 2061.05  1532.1 2065.05    1594 2085.66
#Mann= 14 ,-1,0
       0     .05       0     490     .06       0     550     .05       0
     610     .06       0     730     .05       0     740     .06       0
     840     .05       0     930     .06       0     960     .05       0
    1120      .1       0 1138.09    .045       0  1173.8      .1       0
    1310     .05       0    1420      .1       0
#XS Ineff= 2 , 0
          777.47 2026.34
Permanent Ineff=
       F       F
Bank Sta=1138.09,1173.8
XS Rating Curve= 0 ,0
Exp/Cntr(USF)=0,0
Exp/Cntr=0.3,0.1

Type RM Length L Ch R = 1 ,19541   ,806.5,808.5,809.3
XS GIS Cut Line= 2
2299555.44816842689608.1709397562300430.05046893690849.207405688
#Sta/Elev= 30
       0 2013.14    38.6 2010.38    55.1 2007.88   173.5    2006   192.1 2003.04
   206.8 1998.04   236.1  1995.7   368.2 1995.16   411.7 1993.39   454.8 1994.02
   549.5 1992.43   796.7 1991.01   940.8 1992.13  1143.7 1991.07  1180.6 1988.85
  1188.6 1985.95  1200.1 1984.26  1215.5 1984.66 1219.43  1986.2  1232.7 1997.96
  1244.2 2004.88  1249.1 2006.11  1278.9 2009.33  1332.3 2010.82  1404.9 2018.71
  1420.4 2018.68    1435 2022.35  1459.5 2025.31    1484 2029.74  1518.3 2037.56
#Mann= 18 ,-1,0
       0     .07       0      10     .08       0      90     .07       0
     180     .08       0     210     .06       0     330     .05       0
     450     .06       0     520     .07       0     570     .06       0
     690     .07       0     810     .08       0     860     .07       0
     930     .06       0    1030     .05       0    1050     .07       0
  1188.6    .045       0 1219.43     .07       0    1290     .06       0
Bank Sta=1188.6,1219.43
XS Rating Curve= 0 ,0
Exp/Cntr(USF)=0,0
Exp/Cntr=0.3,0.1

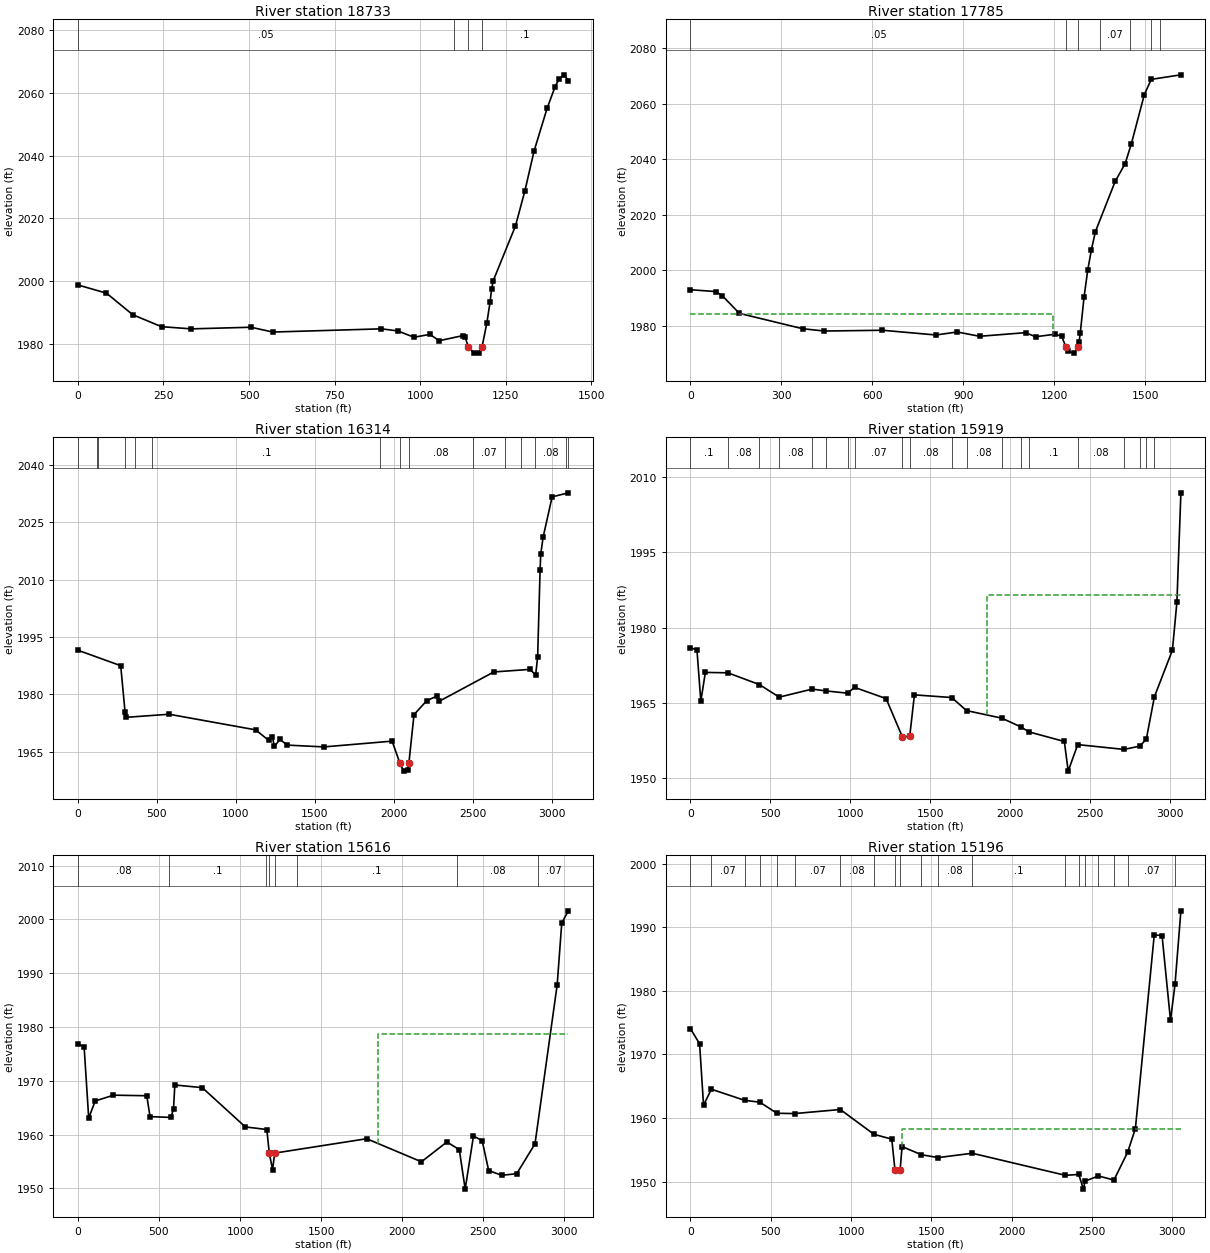
Type RM Length L Ch R = 1 ,18733   ,942.7,948.2,954.3
XS GIS Cut Line= 2
2298985.05536375690009.1743660742299707.55291634691246.753905917
#Sta/Elev= 30
       0 1998.78    83.4 1996.17   160.2 1989.29   244.2 1985.49   331.5 1984.79
   505.3 1985.31   569.5 1983.78   886.8  1984.8   934.4 1984.14     982 1982.12
  1028.3 1983.03    1056 1981.02  1125.5 1982.66  1131.1 1982.19  1140.7 1979.09
  1157.4 1977.06  1171.8 1977.26  1180.8 1979.02    1195 1986.76  1204.3 1993.36
  1208.9 1997.58  1213.5 2000.15  1278.4 2017.55  1306.2 2028.86  1332.9 2041.49
  1370.9 2055.08  1394.3 2061.97    1406 2064.46  1420.6 2065.75    1433 2063.93
#Mann= 4 ,-1,0
       0     .05       0    1100      .1       0  1140.7    .045       0
  1180.8      .1       0
Bank Sta=1140.7,1180.8
XS Rating Curve= 0 ,0
Exp/Cntr(USF)=0,0
Exp/Cntr=0.3,0.1

Type RM Length L Ch R = 1 ,17785   ,1468,1470.7,1472.2
XS GIS Cut Line= 2
2298425.03333734690143.9944835432298791.46750277691720.352780103
#Sta/Elev= 30
       0 1992.93    83.3 1992.26   104.4 1990.83   161.4  1984.4   370.8 1978.85
   441.5 1978.03   633.4 1978.31   810.2  1976.6   880.2 1977.69     954 1976.13
  1105.9 1977.44  1138.8 1975.97  1204.5 1976.89    1225 1976.09  1239.8 1972.11
  1245.5 1970.67  1266.1 1970.06  1278.4 1972.21  1282.5 1974.18  1286.5 1977.45
  1298.9 1990.39  1311.2 2000.15  1323.1 2007.36  1336.4 2013.92  1401.6 2032.02
  1434.4  2038.4    1455 2045.59  1497.8 2063.33  1520.7  2068.8  1618.4 2070.43
#Mann= 7 ,-1,0
       0     .05       0  1239.8    .045       0  1278.4      .1       0
    1350     .07       0    1450     .06       0    1520     .07       0
    1550      .1       0
#XS Ineff= 2 , 0
         1195.05 1984.05
Permanent Ineff=
       F       F
Bank Sta=1239.8,1278.4
XS Rating Curve= 0 ,0
Exp/Cntr(USF)=0,0
Exp/Cntr=0.3,0.1

Type RM Length L Ch R = 1 ,16314   ,391.8,394.6,394.2
BEGIN DESCRIPTION:
Structure XS 4
END DESCRIPTION:
XS GIS Cut Line= 4
2297952.05410387690073.3319230362297247.11361148691074.607779164
2297420.73665779691965.4891280672298390.53228589692040.719388748
#Sta/Elev= 30
       0 1991.53   270.8 1987.49   298.2 1975.39   305.5 1973.97   577.1 1974.78
  1125.1 1970.69  1208.1 1967.93  1231.2 1968.87  1243.5 1966.35  1278.8 1968.21
    1325  1966.7  1557.3 1966.23  1989.2 1967.74  2038.91961.893  2063.2 1959.89
    2087 1960.18 2095.05 1961.89  2127.8 1974.68  2207.8  1978.3  2276.1  1979.6
  2288.1 1978.19  2633.1 1985.85  2861.8 1986.52  2897.9 1985.06  2910.5 1989.81
    2926 2012.54    2930 2016.67  2945.2 2021.13  3002.2 2031.67  3104.9 2032.73
#Mann= 15 ,-1,0
       0     .05       0     120     .07       0     130     .08       0
     300      .1       0     360     .08       0     470      .1       0
 1914.54     .08       0  2038.9    .045       0 2095.05     .08       0
 2502.18     .07       0 2702.18     .08       0 2802.18      .1       0
 2892.18     .08       0 3092.18     .07       0 3102.18     .08       0
Bank Sta=2038.9,2095.05
XS Rating Curve= 0 ,0
Exp/Cntr(USF)=0,0
Exp/Cntr=0.3,0.1

Type RM Length L Ch R = 1 ,15919   ,295.7,303.5,300.3
BEGIN DESCRIPTION:
Structure XS 3 Disconnected without IFA
END DESCRIPTION:
XS GIS Cut Line= 2
2296894.40065793690632.8116801882297216.85741245693681.924814883
#Sta/Elev= 30
       0 1976.01    40.6 1975.52    64.7 1965.33    92.9 1971.09   233.7 1971.01
   430.8 1968.67   554.9 1966.17   760.6 1967.77   848.5  1967.4   981.8 1966.96
  1026.1 1968.11  1223.2 1965.88  1323.7 1958.33  1370.51958.336  1400.1 1966.62
  1633.4 1966.09  1725.9 1963.49    1946 1961.99  2064.5 1960.26  2116.1 1959.25
  2337.4 1957.34  2361.5 1951.44    2421 1956.72  2711.4 1955.76  2810.2 1956.43
  2850.1 1957.84  2900.5 1966.25  3013.1 1975.52  3041.2  1985.1  3066.1 2006.84
#Mann= 20 ,-1,0
       0      .1       0   233.7     .08       0   430.8      .1       0
   554.9     .08       0   760.6      .1       0   848.5     .08       0
   981.8     .08       0  1026.1     .07       0  1323.7    .045       0
  1370.5     .08       0  1633.4      .1       0  1725.9     .08       0
    1946     .07       0  2064.5     .08       0  2116.1      .1       0
    2421     .08       0  2711.4     .07       0  2810.2     .08       0
  2850.1      .1       0  2900.5     .08       0
#XS Ineff= 2 , 0
                         1851.92         1986.52
Permanent Ineff=
       F       F
Bank Sta=1323.7,1370.5
XS Rating Curve= 0 ,0
Exp/Cntr(USF)=0,0
Exp/Cntr=0.3,0.1

Type RM Length L Ch R = 1 ,15616   ,415.7,419.5,416.7
BEGIN DESCRIPTION:
Structure XS 2 Disconnected without IFA
END DESCRIPTION:
XS GIS Cut Line= 2
2296619.36401436690699.1998355312296956.04680218693705.634870362
#Sta/Elev= 30
       0  1976.9    38.2 1976.28    66.4 1963.08   106.6 1966.26   219.3 1967.34
   424.6 1967.23   444.7 1963.35   573.5  1963.2   589.6 1964.77   597.7 1969.23
   766.7 1968.74  1032.4 1961.44  1165.2 1960.95  1180.41956.538  1200.6  1953.5
 1213.981956.568    1781 1959.24  2119.1 1954.95  2276.1 1958.64  2352.6  1957.2
  2388.8 1949.87  2439.9 1959.75  2493.5 1958.88  2533.7 1953.33  2614.2 1952.44
  2706.8 1952.74  2819.5  1958.3  2956.2 1987.84  2984.5 1999.34  3025.2 2001.61
#Mann= 8 ,-1,0
       0     .08       0     560      .1       0    1160     .08       0
  1180.4    .045       0 1213.98     .08       0    1350      .1       0
    2340     .08       0    2840     .07       0
#XS Ineff= 2 , 0
                         1852.35         1978.62
Permanent Ineff=
       F       F
Bank Sta=1180.4,1213.98
XS Rating Curve= 0 ,0
Exp/Cntr(USF)=0,0
Exp/Cntr=0.3,0.1

Type RM Length L Ch R = 1 ,15196   ,317.9,307,315.3
BEGIN DESCRIPTION:
Structure XS 1 Disconnected without IFA
END DESCRIPTION:
XS GIS Cut Line= 4
2296509.38565747690733.4601505822296336.73380184691597.730574673
2296397.63182704692471.1833409742296597.62841379693753.151558887
#Sta/Elev= 30
       0 1974.02    56.8 1971.67    81.3 1962.01   130.2 1964.52   337.4 1962.77
   432.1 1962.48   538.1 1960.74   648.3 1960.69   933.1 1961.33  1142.7 1957.43
  1253.7 1956.67 1273.43 1951.84  1305.8 1951.88  1317.9  1955.5  1438.1 1954.22
  1542.4 1953.77  1754.9 1954.45  2335.2 1950.98  2418.2 1951.12  2447.2 1948.81
  2457.8 1950.07  2540.3 1950.88  2637.4 1950.24  2722.5  1954.6    2771 1958.33
  2888.4 1988.77    2937 1988.69  2989.6 1975.36  3017.8    1981  3054.4 1992.57
#Mann= 20 ,-1,0
       0     .08       0   130.2     .07       0   337.4     .06       0
   432.1     .07       0   538.1     .06       0   648.3     .07       0
   933.1     .08       0  1142.7     .07       0 1273.43    .045       0
  1305.8     .08       0  1438.1      .1       0  1542.4     .08       0
  1754.9      .1       0  2335.2     .08       0  2418.2     .07       0
  2457.8     .08       0  2540.3     .07       0  2637.4     .06       0
  2722.5     .07       0  3017.8     .08       0
#XS Ineff= 2 , 0
                          1318.2         1958.21
Permanent Ineff=
       F       F
Bank Sta=1273.43,1305.8
XS Rating Curve= 0 ,0
Exp/Cntr(USF)=0,0
Exp/Cntr=0.3,0.1

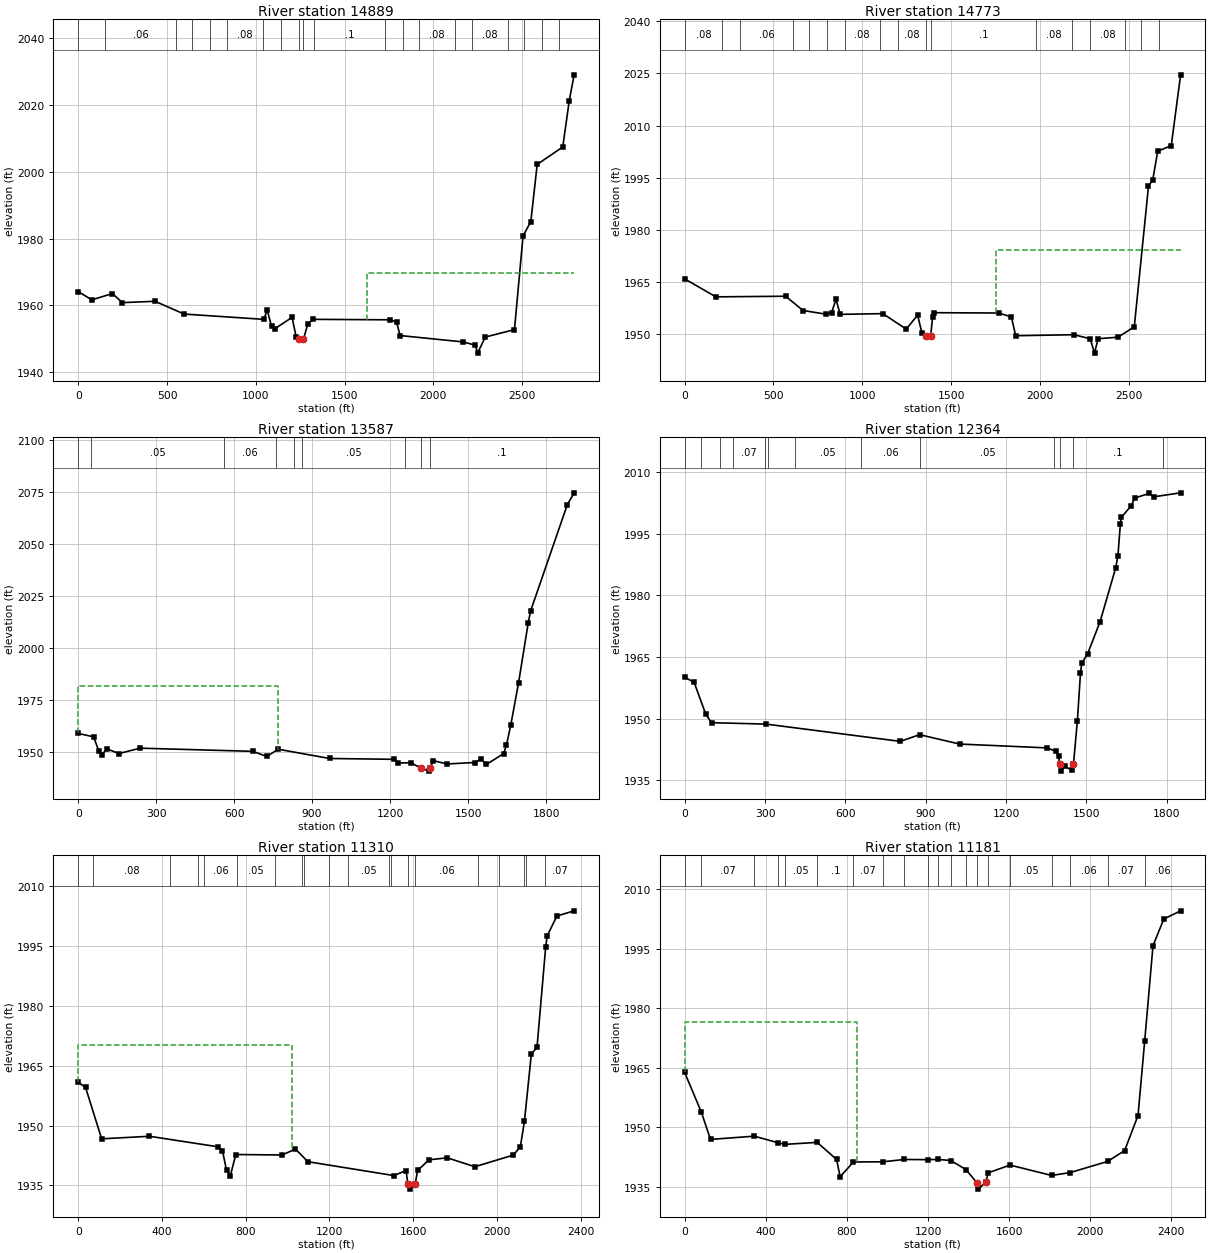
Type RM Length L Ch R = 1 ,14889   ,106.4,116,106.2
XS GIS Cut Line= 2
2296098.54268014690908.6793348952296131.96893238693701.290772378
#Sta/Elev= 30
       0 1964.18    76.5 1961.68   192.5 1963.58   248.5 1960.86   432.5 1961.26
   596.5 1957.43  1044.6 1955.85  1064.6 1958.57  1088.6 1953.72  1108.6 1953.09
  1204.6 1956.45  1227.5 1950.52 1243.73 1949.87  1268.6 1949.86  1292.6 1954.49
  1324.6 1955.85  1756.6 1955.71  1792.6 1955.06  1812.6    1951  2164.7  1949.1
  2236.7 1948.13  2248.7 1945.73  2292.7 1950.55  2456.7 1952.78    2505 1980.85
  2548.7 1985.13  2584.7 2002.26  2728.7  2007.5  2765.2 2021.37  2792.8  2029.1
#Mann= 20 ,-1,0
       0      .1       0     150     .06       0     550     .07       0
     640      .1       0     740     .07       0     840     .08       0
    1040     .07       0    1140     .08       0 1243.73    .045       0
  1268.6     .08       0    1330      .1       0    1730     .08       0
    1830      .1       0    1920     .08       0    2120     .07       0
    2220     .08       0    2420     .07       0    2510     .08       0
    2610     .03       0    2710     .06       0
#XS Ineff= 2 , 0
                         1628.25         1969.61
Permanent Ineff=
       F       F
Bank Sta=1243.73,1268.6
XS Rating Curve= 0 ,0
Exp/Cntr(USF)=0,0
Exp/Cntr=0.3,0.1

Type RM Length L Ch R = 1 ,14773   ,1165.3,1186.5,1193.5
XS GIS Cut Line= 2
2296008.89954912690849.4237059172296042.32580136  693642.0351434
#Sta/Elev= 30
       0 1965.95   175.8 1960.79   568.3 1960.97   667.1 1956.86   795.8 1955.82
   827.8 1956.26   851.8 1960.11   875.8 1955.76  1115.8 1955.97  1247.8 1951.52
  1311.8 1955.55  1335.1 1950.54  1360.61949.438 1385.09 1949.45  1395.9 1954.89
  1403.9 1956.24  1767.9 1956.14  1839.9 1955.04  1863.9 1949.62  2191.9 1949.91
  2283.9 1948.75  2307.9 1944.62  2327.9 1948.77  2439.9 1949.19  2531.9 1952.19
  2611.9 1992.59  2635.9 1994.42  2663.9 2002.65    2740 2004.23  2792.8 2024.59
#Mann= 17 ,-1,0
       0     .08       0     210     .07       0     310     .06       0
     610     .07       0     700      .1       0     800     .07       0
     900     .08       0    1100     .07       0    1200     .08       0
  1360.6    .045       0 1385.09      .1       0    1980     .08       0
    2180     .07       0    2280     .08       0    2480     .07       0
    2570     .08       0    2670     .06       0
#XS Ineff= 2 , 0
                         1754.65         1974.31
Permanent Ineff=
       F       F
Bank Sta=1360.6,1385.09
XS Rating Curve= 0 ,0
Exp/Cntr(USF)=0,0
Exp/Cntr=0.3,0.1

Type RM Length L Ch R = 1 ,13587   ,1178.9,1222.3,1218.4
XS GIS Cut Line= 4
2295441.61395432691697.0037467392295568.63451732692262.052146843
2295354.69573613693312.8183154452295220.66216024693531.752541869
#Sta/Elev= 30
       0 1958.93    59.2 1957.29    79.3 1950.48    90.4 1948.68   110.9 1951.54
     156 1949.25     238 1951.85   672.1 1950.33   725.2 1947.88   770.1 1951.33
     967  1946.9  1216.4  1946.5  1231.4 1944.75  1280.4 1944.82  1317.1 1942.38
  1349.8 1940.83 1354.811942.325  1365.6 1945.87  1419.2 1944.27  1525.7 1944.97
  1549.8 1946.57  1570.2 1944.03    1637 1949.24  1647.8 1953.43    1664 1962.76
  1694.3  1983.2  1731.6 2012.12  1740.8 2017.78  1881.7 2068.68  1908.2 2074.43
#Mann= 9 ,-1,0
       0     .06       0      50     .05       0     560     .06       0
  759.15     .07       0  829.15     .06       0  859.15     .05       0
 1259.15      .1       0  1317.1    .045       0 1354.81      .1       0
#XS Ineff= 2 , 0
          768.23 1981.76
Permanent Ineff=
       F       F
Bank Sta=1317.1,1354.81
XS Rating Curve= 0 ,0
Exp/Cntr(USF)=0,0
Exp/Cntr=0.3,0.1

Type RM Length L Ch R = 1 ,12364   ,1024.4,1054,1074.9
BEGIN DESCRIPTION:
Structure XS 4
END DESCRIPTION:
XS GIS Cut Line= 3
2295293.29380546691699.5460442662294470.54539629692947.496362375
2294570.79625287693289.732045181
#Sta/Elev= 30
       0  1960.1    35.5 1958.78    78.6 1951.06   100.2 1948.99   303.8 1948.64
   804.7 1944.43   876.9 1946.06  1026.7 1943.78    1353 1942.84  1386.6 1941.99
  1396.2 1940.75 1399.891938.965  1405.7 1937.18  1419.7 1938.32  1444.1 1937.46
  1451.5 1938.91  1465.9  1949.4  1477.6 1961.08  1482.4 1963.52  1503.9 1965.72
  1550.7  1973.6    1609 1986.71  1617.4 1989.68  1626.4 1997.35  1629.9 1999.03
  1667.4 2001.86  1679.9 2003.74  1734.1 2004.84  1750.8 2004.03  1851.4    2005
#Mann= 13 ,-1,0
       0     .05       0      60     .07       0     130     .08       0
     180     .07       0     300     .05       0     310     .07       0
     410     .05       0     660     .06       0     880     .05       0
    1380      .1       0 1399.89    .045       0  1451.5      .1       0
 1784.76     .05       0
Bank Sta=1399.89,1451.5
XS Rating Curve= 0 ,0
Exp/Cntr(USF)=0,0
Exp/Cntr=0.3,0.1

Type RM Length L Ch R = 1 ,11310   ,128.6,129.7,129.7
BEGIN DESCRIPTION:
Structure XS 3
END DESCRIPTION:
XS GIS Cut Line= 6
2295276.00917501691671.8906355542294394.49302233692363.275853344
2293865.58333072692169.6879923632293675.45239583692121.291027117
2293464.57990441692107.4633227612293395.44138263692377.103557699
#Sta/Elev= 30
       0 1960.82      35 1959.56   111.9 1946.67   340.4 1947.31   669.7 1944.66
   689.1 1943.72   708.6 1938.81   726.7  1937.4   752.9 1942.74   974.3 1942.62
  1037.8 1944.11  1097.5 1940.94  1507.5 1937.47  1566.7 1938.72    1575 1935.28
  1583.6 1934.07  1609.7 1935.26  1621.7 1938.78  1676.7 1941.42  1763.6 1941.91
  1895.2 1939.68  2079.6 1942.61  2112.7 1944.73  2131.9 1951.02  2165.2 1967.95
  2192.1 1969.59  2233.4  1994.6  2240.8 1997.53  2287.4 2002.49  2369.6 2003.78
#Mann= 20 ,-1,0
       0     .05       0      70     .08       0     440     .07       0
     570     .05       0     600     .06       0     760     .05       0
     940     .06       0    1070     .07       0    1080     .05       0
 1200.31     .06       0 1290.31     .05       0 1484.61     .06       0
 1494.61     .07       0    1575    .045       0  1609.7     .06       0
 1909.87     .05       0 2009.87     .07       0 2131.19     .06       0
 2141.19     .03       0 2231.19     .07       0
#XS Ineff= 2 , 0
         1023.47 1970.14
Permanent Ineff=
       F       F
Bank Sta=1575,1609.7
XS Rating Curve= 0 ,0
Exp/Cntr(USF)=0,0
Exp/Cntr=0.3,0.1

Type RM Length L Ch R = 1 ,11181   ,928,915.7,897.4
BEGIN DESCRIPTION:
Structure XS 2
END DESCRIPTION:
XS GIS Cut Line= 6
2295189.58602279691547.4412963522294346.09605709692197.343401074
2293875.95410899692041.781727072 2293654.7108393 692014.12631836
2293326.30286085691996.8416879152293250.25048689692321.792740276
#Sta/Elev= 30
       0 1963.77    82.1 1953.78   127.4 1946.89   343.6 1947.71   461.4 1946.03
   494.4 1945.64   653.2 1946.14   749.1 1941.84   766.6 1937.47   832.2  1941.2
   976.4 1941.24  1082.2 1941.83  1198.5 1941.78  1248.9 1941.84  1311.9 1941.57
  1387.6 1939.26 1440.421935.987  1446.4 1934.35 1484.751936.022  1496.7 1938.46
  1604.2 1940.42  1809.6  1937.8  1900.5 1938.52    2086 1941.34  2169.7 1944.09
  2235.5 1952.91  2268.3 1971.63  2309.4 1995.77  2362.8 2002.48  2445.6 2004.55
#Mann= 20 ,-1,0
       0     .08       0    82.1     .07       0   343.6     .08       0
   461.4     .07       0   494.4     .05       0   653.2      .1       0
   832.2     .07       0   976.4     .05       0  1082.2     .07       0
  1198.5     .06       0  1248.9     .05       0  1311.9     .07       0
  1387.6     .05       0 1440.42    .045       0  1496.7     .07       0
  1604.2     .05       0  1809.6     .08       0  1900.5     .06       0
    2086     .07       0  2268.3     .06       0
#XS Ineff= 2 , 0
          848.38 1976.48
Permanent Ineff=
       F       F
Bank Sta=1440.42,1484.75
XS Rating Curve= 0 ,0
Exp/Cntr(USF)=0,0
Exp/Cntr=0.3,0.1

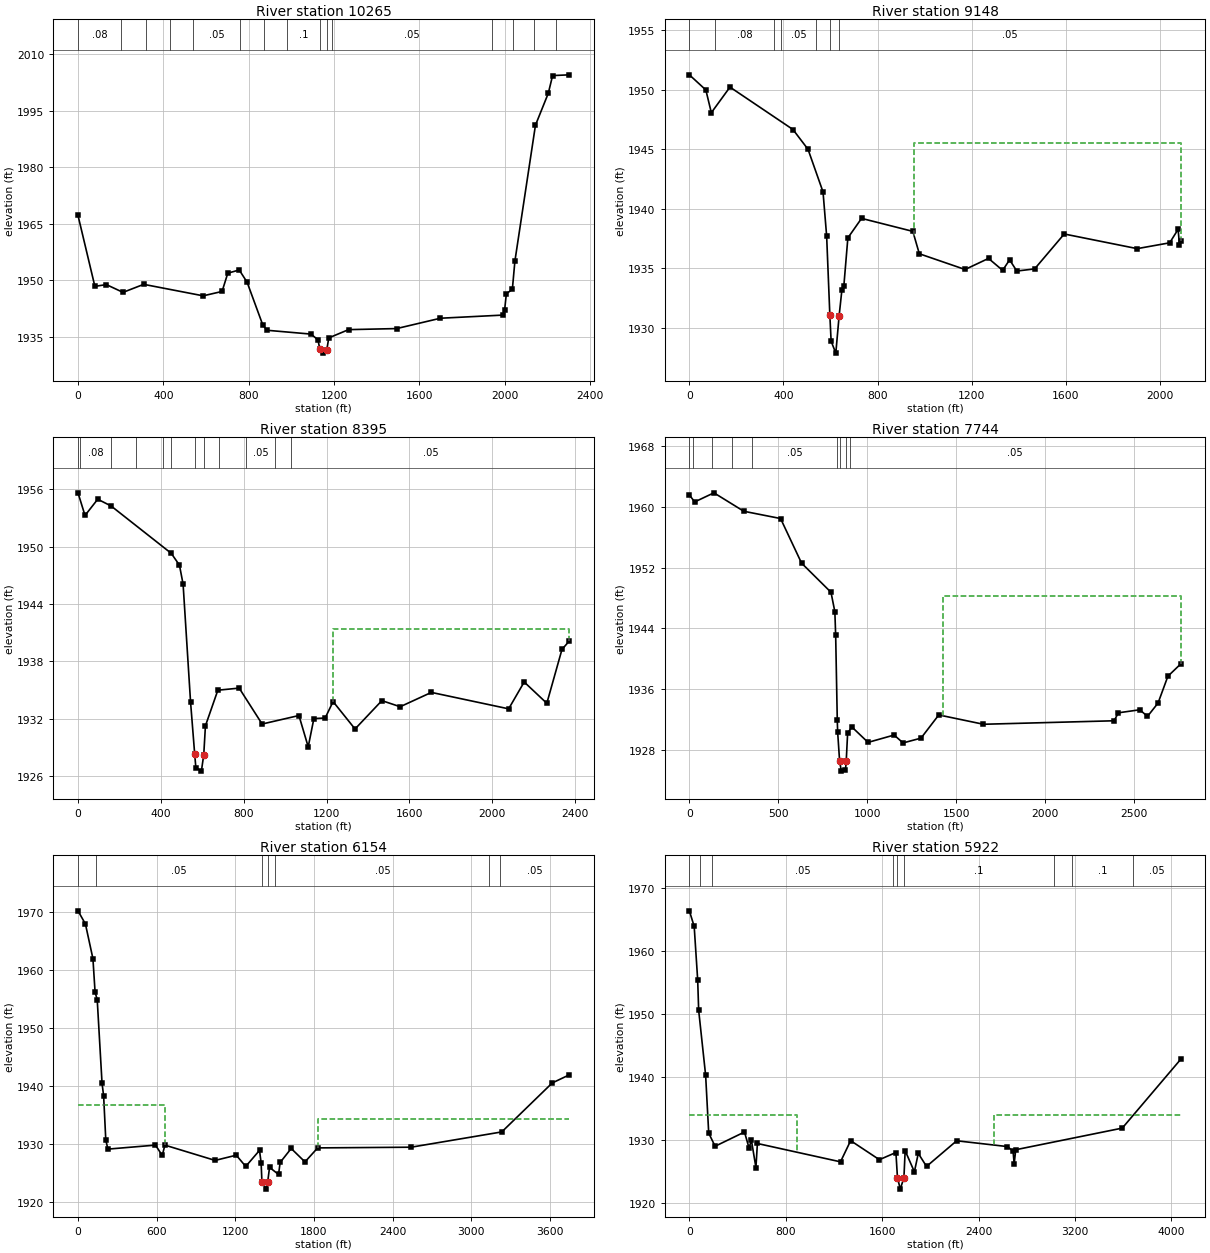
Type RM Length L Ch R = 1 ,10265   ,1113,1117,1106.2
BEGIN DESCRIPTION:
Structure XS 4 and 1
END DESCRIPTION:
XS GIS Cut Line= 3
2294714.66096617691011.9164992642293076.03268746691844.402891664
2293112.91499598692308.066198824
#Sta/Elev= 30
       0 1967.23    79.1 1948.45   132.9 1948.91     211 1946.86   307.9 1948.98
   586.5 1945.94   675.2  1947.1   701.9 1951.93   755.5 1952.79   792.4 1949.55
   865.6 1938.28   885.9 1936.82  1091.7 1935.81  1124.4 1934.31  1133.6 1931.74
  1148.2 1930.77  1166.1 1931.68    1175  1934.8    1268 1936.99  1493.3 1937.27
  1698.4 1940.01  1991.2 1940.84  1999.3 1942.25  2007.3  1946.5  2035.4 1947.65
  2047.4 1955.16  2143.7 1991.12  2203.9 1999.58    2224 2004.25  2303.1 2004.45
#Mann= 15 ,-1,0
       0     .08       0     200     .07       0     320     .08       0
     430     .06       0     540     .05       0     760      .1       0
     870     .05       0     980      .1       0  1133.6    .045       0
  1166.1      .1       0    1190     .05       0 1937.97     .06       0
 2037.97      .1       0 2137.97     .06       0 2237.97     .07       0
Bank Sta=1133.6,1166.1
XS Rating Curve= 0 ,0
Exp/Cntr(USF)=0,0
Exp/Cntr=0.3,0.1

Type RM Length L Ch R = 1 ,9148    ,754.6,753.2,751.8
BEGIN DESCRIPTION:
Structure XS 3
END DESCRIPTION:
XS GIS Cut Line= 2
2294024.43490665690326.9593409612292391.07552915691628.377941738
#Sta/Elev= 30
       0 1951.25    70.1 1949.98    93.4 1948.07   172.6 1950.22   440.2 1946.66
   504.2    1945     568 1941.42   583.4 1937.71  596.971931.081   602.4 1928.89
   622.3 1927.89   636.5 1931.04   647.9 1933.15   656.5 1933.54   673.5 1937.56
   731.7  1939.2   949.6 1938.11   977.2 1936.23  1171.5 1934.91  1271.2 1935.84
  1331.1 1934.84  1360.8 1935.72  1391.5 1934.78  1467.1 1934.96  1592.9 1937.89
  1902.9 1936.66    2041 1937.15  2076.8 1938.28  2082.5 1936.99  2088.4 1937.28
#Mann= 7 ,-1,0
       0     .07       0     110     .08       0     360     .07       0
     390     .05       0     540     .03       0  596.97    .045       0
   636.5     .05       0
#XS Ineff= 2 , 0
                          954.87         1945.53
Permanent Ineff=
       F       F
Bank Sta=596.97,636.5
XS Rating Curve= 0 ,0
Exp/Cntr(USF)=0,0
Exp/Cntr=0.3,0.1

Type RM Length L Ch R = 1 ,8395    ,658.5,650.7,645.2
BEGIN DESCRIPTION:
Structure XS 2
END DESCRIPTION:
XS GIS Cut Line= 3
2293455.39357513689768.455811882 2291930.8150407691180.731226616
2291947.19246017691474.320917142
#Sta/Elev= 30
       0 1955.63    33.9 1953.26    95.2 1954.96     160 1954.25     450  1949.3
   489.7 1948.06   507.3 1946.07   543.4 1933.71   563.41928.241   568.9 1926.86
   595.6  1926.5     6071928.215   615.1 1931.24     675 1934.97     778 1935.19
   888.7 1931.43  1066.4 1932.32  1111.2 1929.04  1138.5    1932    1193 1932.06
  1231.2 1933.78  1337.2 1930.91  1466.7 1933.88    1555 1933.24  1705.6 1934.74
  2078.6 1933.02  2153.6 1935.83  2262.9  1933.6    2336 1939.24  2372.2 1940.14
#Mann= 12 ,-1,0
       0     .07       0      10     .08       0     160     .07       0
     280     .06       0     410     .05       0     450      .1       0
   563.4    .045       0     607     .06       0     680      .1       0
     810     .05       0     950      .1       0    1030     .05       0
#XS Ineff= 2 , 0
                         1232.96         1941.35
Permanent Ineff=
       F       F
Bank Sta=563.4,607
XS Rating Curve= 0 ,0
Exp/Cntr(USF)=0,0
Exp/Cntr=0.3,0.1

Type RM Length L Ch R = 1 ,7744    ,1573.9,1589.8,1573.4
BEGIN DESCRIPTION:
Structure XS 1
END DESCRIPTION:
XS GIS Cut Line= 4
2293070.76378624689231.0278876752292696.67179978 689425.97723273
2291743.00067937 691159.445733362291864.18540738691501.924312512
#Sta/Elev= 30
       0 1961.61      30 1960.69   138.2 1961.89     306 1959.46   512.9  1958.5
   630.9 1952.62   796.3 1948.78   818.1 1946.22   822.7  1943.1   831.8 1931.89
   833.9 1930.33   844.8 1926.54   854.4 1925.19   877.5 1925.28     882 1926.47
   889.9 1930.18   913.5 1931.02  1004.8 1928.98  1151.4 1929.95  1201.6 1928.91
  1302.5 1929.54  1402.5  1932.6  1653.6 1931.37  2388.6 1931.83    2412 1932.88
  2532.6 1933.28  2576.1 1932.41  2635.5 1934.17  2690.7  1937.7  2763.6 1939.34
#Mann= 9 ,-1,0
       0     .06       0      20     .08       0     130     .07       0
     240     .06       0     350     .05       0  831.84     .06       0
   844.8    .045       0     882     .06       0  901.84     .05       0
#XS Ineff= 2 , 0
                         1425.27         1948.24
Permanent Ineff=
       F       F
Bank Sta=844.8,882
XS Rating Curve= 0 ,0
Exp/Cntr(USF)=0,0
Exp/Cntr=0.3,0.1

Type RM Length L Ch R = 1 ,6154    ,226.9,232,234.2
XS GIS Cut Line= 6
2292011.71464148688730.4822719912291584.93364284688820.053592692
 2291363.6397917690527.1775872342291310.95077952690869.656166386
2291231.91726125 691090.950017532291985.37013539691765.369373398
#Sta/Elev= 30
       0 1970.22    56.7 1967.95     114 1961.96   130.3 1956.18   146.7 1954.89
   183.5 1940.45   195.7 1938.25   212.1 1930.64   228.4 1929.07   591.3 1929.76
   642.9 1927.97   663.1 1929.76  1046.3 1927.12  1207.6 1928.02  1279.9 1926.08
  1385.1 1928.85  1397.2 1926.73 1403.43 1923.46  1437.7 1922.16 1447.661923.441
  1461.7 1925.92  1530.3 1924.69  1542.4 1926.76  1626.8 1929.18    1732 1926.86
  1828.8 1929.28  2541.7  1929.4  3233.6 1932.04  3618.9  1940.5  3750.2 1941.91
#Mann= 7 ,-1,0
       0      .1       0     140     .05       0 1403.43    .045       0
 1447.66      .1       0 1506.08     .05       0 3138.98      .1       0
 3218.98     .05       0
#XS Ineff= 2 , 0
          664.24 1936.68 1828.17         1934.26
Permanent Ineff=
       F       F
Bank Sta=1403.43,1447.66
XS Rating Curve= 0 ,0
Exp/Cntr(USF)=0,0
Exp/Cntr=0.3,0.1

Type RM Length L Ch R = 1 ,5922    ,1510.5,1507.3,1495.6
XS GIS Cut Line= 6
 2291959.0256293688604.0286427662291432.13550753688741.020074427
2291210.84165638690427.0684640972291152.88374299690806.429351773
 2291036.9679162691101.4878199662291874.72320982691865.478496535
#Sta/Elev= 30
       0 1966.31    40.1 1963.84    69.1 1955.35    77.3 1950.53   135.2  1940.2
   160.7 1931.04   213.7 1928.96   457.6 1931.22   494.8 1928.73   515.4 1929.88
   552.6 1925.58   564.7  1929.4  1254.6 1926.49  1338.7 1929.85  1577.4 1926.83
  1714.5 1927.97  1727.3 1923.99  1750.8 1922.16 1781.04 1923.99  1791.2 1928.26
  1867.8 1924.91  1900.1 1927.83  1968.7 1925.76  2218.8 1929.83  2640.2 1928.91
  2686.9 1928.18  2696.1 1926.16    2709 1928.41  3593.3 1931.84  4079.5 1942.78
#Mann= 9 ,-1,0
       0      .1       0      90     .06       0     190     .05       0
 1694.41      .1       0  1727.3    .045       0 1781.04      .1       0
 3025.69     .05       0 3175.69      .1       0 3685.69     .05       0
#XS Ineff= 2 , 0
          890.21 1933.93 2530.55         1933.94
Permanent Ineff=
       F       F
Bank Sta=1727.3,1781.04
XS Rating Curve= 0 ,0
Exp/Cntr(USF)=0,0
Exp/Cntr=0.3,0.1