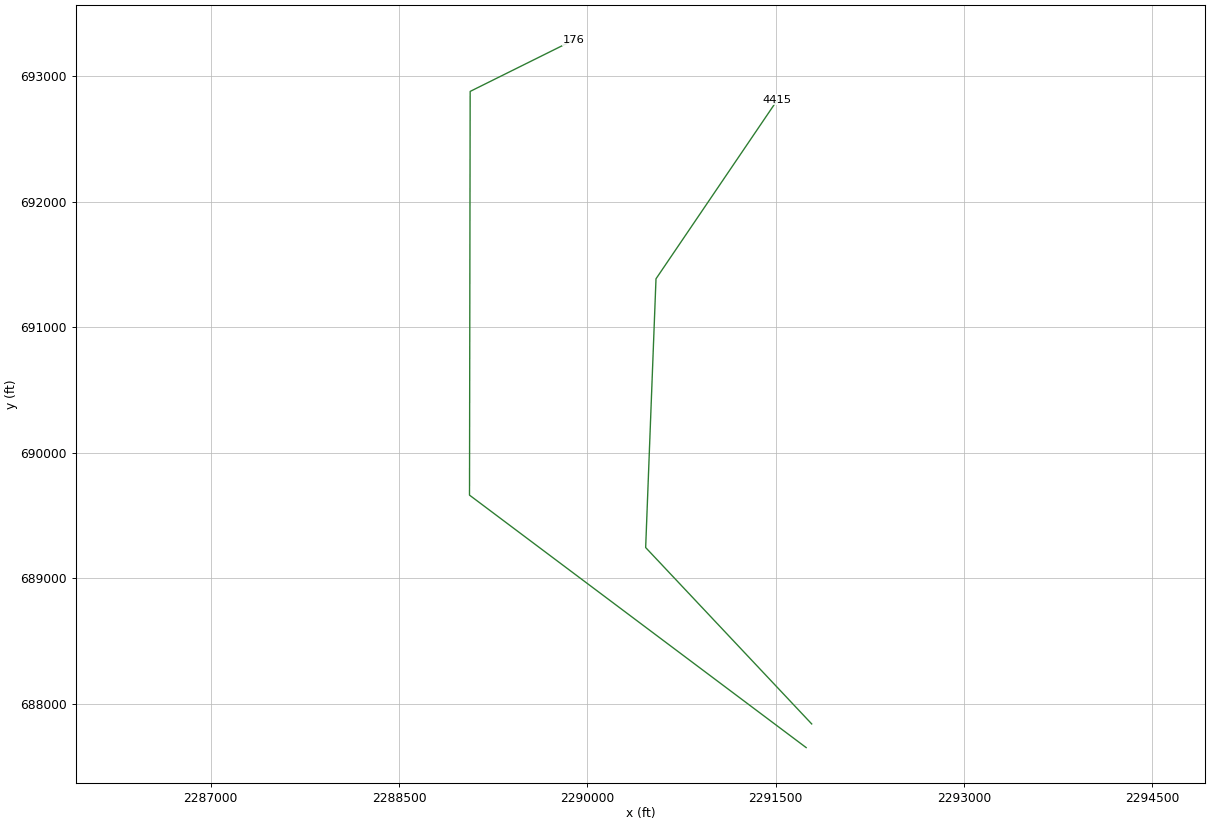
HEC-RAS study CHENOWTHCK.prj: CHENOWTHCK

--- CHENOWTHCK.g01 (geometry) --- (continued)

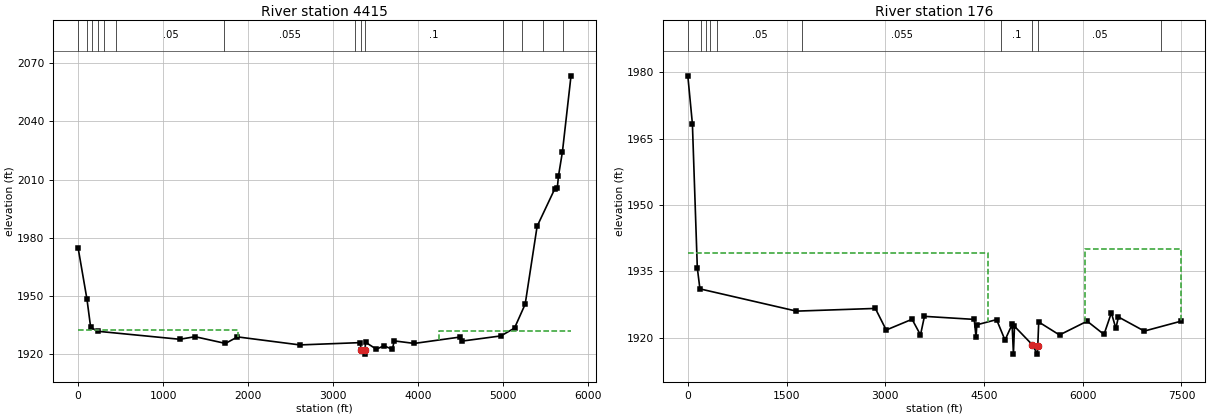
Type RM Length L Ch R = 1 ,4415    ,4148.2,4239.6,3975.8
XS GIS Cut Line= 4
2291787.70549333687839.5935234092290465.14490394689244.492515252
2290547.48330639691385.2909790142291514.95953521 692810.77457147
#Sta/Elev= 30
       0 1974.98   104.4 1948.49   147.9    1934   232.7 1931.91  1195.6  1927.8
    1376 1929.12  1732.6 1925.66  1874.1 1929.02  2607.6 1924.89  3315.2 1926.07
 3326.93 1922.45  3367.2 1920.15  3372.7 1922.44    3380 1926.25  3507.3 1922.67
  3595.4 1924.48  3695.5 1922.58  3715.5 1926.97  3952.9 1925.66  4493.3 1928.96
  4512.9 1926.86  4970.6 1929.53  5130.4 1933.55  5255.9 1945.88  5396.3 1985.97
  5601.4 2005.02  5633.2 2005.57  5647.2 2011.81  5693.8 2024.32  5794.7 2063.44
#Mann= 14 ,-1,0
       0      .1       0     100     .08       0     160      .1       0
     230     .07       0     300     .08       0     450     .05       0
    1720    .055       0 3259.48     .08       0 3326.93    .045       0
  3372.7      .1       0 4991.87     .05       0 5221.87      .1       0
 5461.87     .06       0 5701.87      .1       0
#XS Ineff= 2 , 0
         1881.63 1932.62  4246.4         1931.91
Permanent Ineff=
       F       F
Bank Sta=3326.93,3372.7
XS Rating Curve= 0 ,0
Exp/Cntr(USF)=0,0
Exp/Cntr=0.3,0.1

Type RM Length L Ch R = 1 ,176     ,,,
BEGIN DESCRIPTION:
Structure XS 1
END DESCRIPTION:
XS GIS Cut Line= 4
2291743.57537347687651.2098932522289062.04007234689661.992601222
2289067.19680659692877.9020806412289892.65799737693287.705508686
#Sta/Elev= 30
       0 1979.23    69.6 1968.38   144.2 1935.82   183.8 1931.07  1650.1 1926.04
  2849.1 1926.65  3014.1 1921.77  3406.9  1924.2  3534.9 1920.66  3594.9 1924.86
  4351.4 1924.17  4378.9 1920.12  4390.9 1922.95  4690.9 1924.12  4818.9  1919.5
  4926.9 1923.03  4946.9 1916.35  4962.9 1922.625234.815 1918.42  5310.9 1916.32
 5317.051918.252  5330.9 1923.59  5646.9 1920.65  6066.9 1923.77  6322.9 1920.77
  6434.9 1925.66  6502.9 1922.14  6541.9 1924.72  6934.9 1921.53  7489.2 1923.75
#Mann= 10 ,-1,0
       0      .1       0     200     .05       0     270     .07       0
     330     .08       0     450     .05       0    1740    .055       0
  4751.7      .1       05234.815    .045       0 5317.05     .05       0
 7187.61      .1       0
#XS Ineff= 2 , 0
          4557.4 1939.21  6036.1         1940.05
Permanent Ineff=
       F       F
Bank Sta=5234.815,5317.05
XS Rating Curve= 0 ,0
Exp/Cntr(USF)=0,0
Exp/Cntr=0.3,0.1
LCMann Table=0

Chan Stop Cuts=-1
Use User Specified Reach Order=0
Composite Channel Slope=5